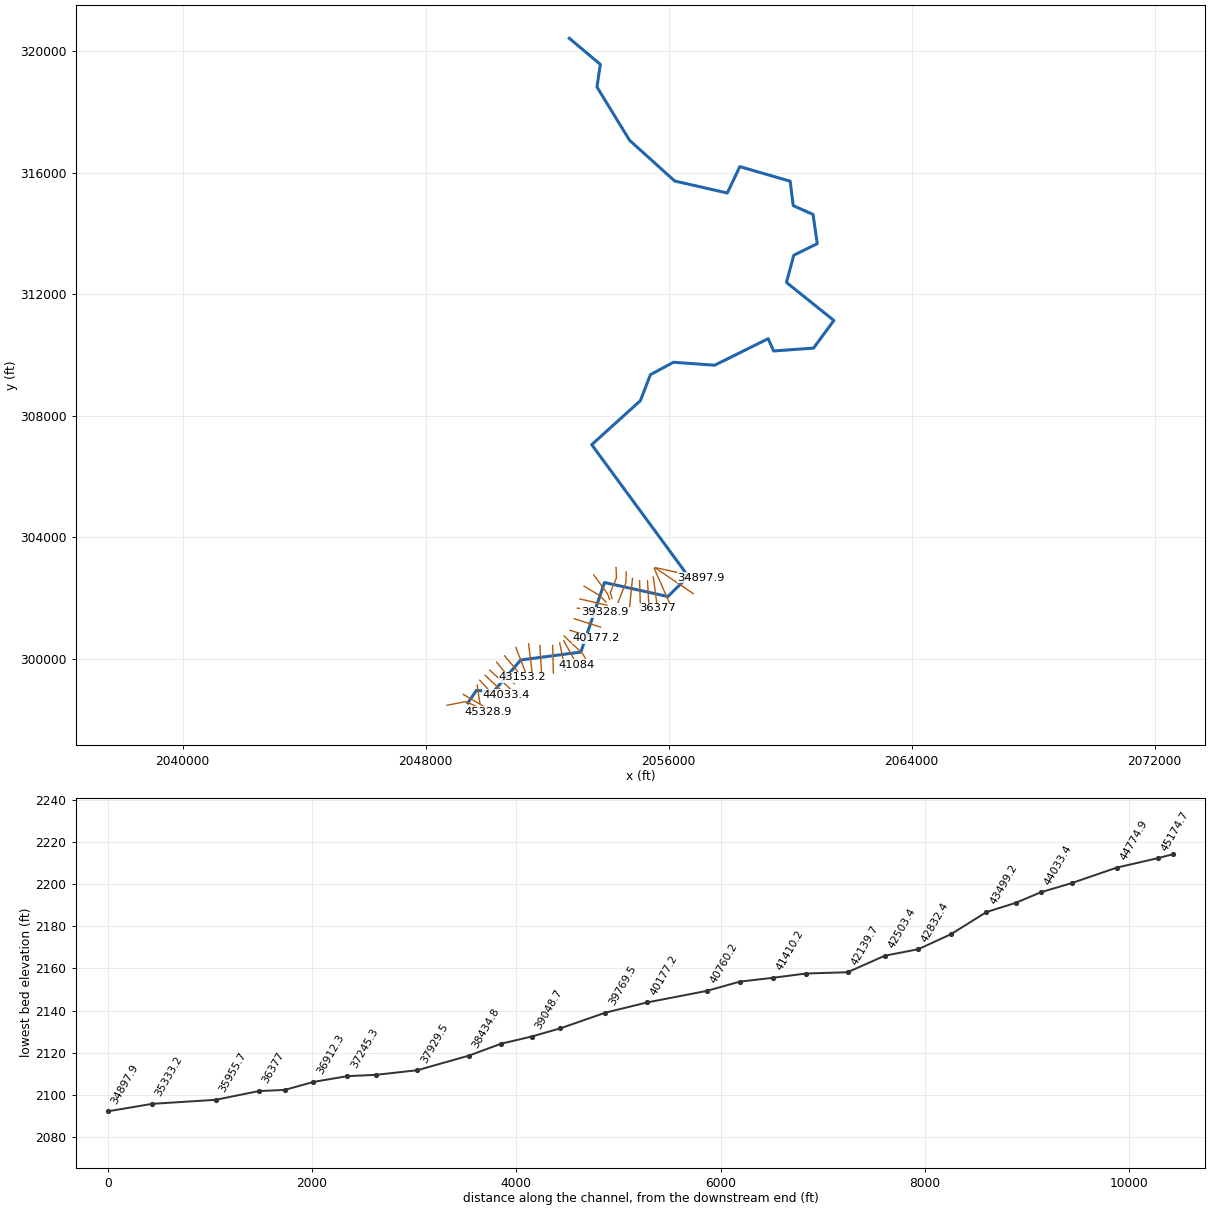
--- ABRMCRK.prj (project) ---

Proj Title=ABRMCRK
Current Plan=p01
Default Exp/Contr=0,0
English Units
Geom File=g01
Flow File=f01
Plan File=p01
BEGIN DESCRIPTION:
END DESCRIPTION:
DSS Export Rating Curves= 0
DSS Export Rating Curve Sorted= 0
DSS Export Volume Flow Curves= 0
DXF OffsetX= 0
DXF OffsetY= 0
DXF ScaleX= 0
DXF ScaleY= 0

--- ABRMCRK.p01 (plan) ---

Plan Title=Floodplain
Program Version=4.00
Geom File=g01
Flow File=f01
K Sum by GR=0
Std Step Tol=0.01
Critical Tol=0.01
Num of Std Step Trials=20
Max Error Tol=0.3
Flow Tol Ratio=0.001
Split Flow NTrial=30
Split Flow Tol=0.02
Split Flow Ratio=0.02
Log Output Level=0
Friction Slope Method=1
Unsteady Friction Slope Method=2
Unsteady Bridges Friction Slope Method=1
Global Log Level=0
CheckData=False
Run HTab=0
Run UNet=0
Run PostProcess=0
UNET Theta=0
UNET Theta Warmup=0
UNET ZTol=0
UNET ZSATol=0
UNET MxIter=0
UNET MaxInSteps=0
UNET DtIC=0
UNET DtMin=0
UNET MaxCRTS=0
UNET WFStab=0
UNET SFStab=0
UNET WFX=0
UNET SFX=0
UNET DSS MLevel=0
UNET DZMax Abort=0
UNET Convert EG Bridges=0
UNET Use Existing IB Tables=0
UNET Froude Limit=0
UNET Froude Power=0
Write IC File=0
Echo Input=False
Echo Output=False
Write Detailed=0

--- ABRMCRK.f01 (steady flow) ---

Flow Title=NFF Regression Equation
Program Version=4.00
Number of Profiles= 1
Profile Names=P100yr
River Rch & RM=ABRMCRK,Main            ,45328.9
    4489
River Rch & RM=ABRMCRK,Main            ,28560
    4904
River Rch & RM=ABRMCRK,Main            ,18407.3
    5379
River Rch & RM=ABRMCRK,Main            ,17508.3
    6166
River Rch & RM=ABRMCRK,Main            ,152.8
    6605
Boundary for River Rch & Prof#=ABRMCRK,Main            , 1
Up Type= 0
Dn Type= 3
Dn Slope=0.01863
DSS Import GetInterval= 0
DSS Import GetPeak= 0
DSS Import FillOption= 0

--- ABRMCRK.g01 (geometry) ---

Geom Title=USGS 10m DEM
Program Version=4.00

River Reach=ABRMCRK         ,Main
Reach XY= 30
     2049389.643      298554.952     2049672.098       298965.53
     2050232.619      298924.708     2051128.724      299965.603
     2053108.498      300224.838     2053887.334      302513.725
     2055972.873      302054.207     2056650.025      302714.516
     2053466.487      307050.444     2055068.089      308497.387
     2055400.192      309354.932     2056159.053      309762.237
     2057515.494      309665.718     2059276.656      310538.192
     2059456.202      310134.442     2060769.659       310228.63
     2061439.917      311137.919     2059878.671      312390.618
     2060119.423      313284.289      2060894.25      313666.638
      2060753.68      314628.049     2060099.836      314916.934
      2060001.91      315720.789     2058342.523      316199.306
      2057930.45      315332.342     2056198.996      315726.728
     2054714.251      317066.224     2053639.095        318821.4
     2053750.283      319565.776     2052727.968      320424.759

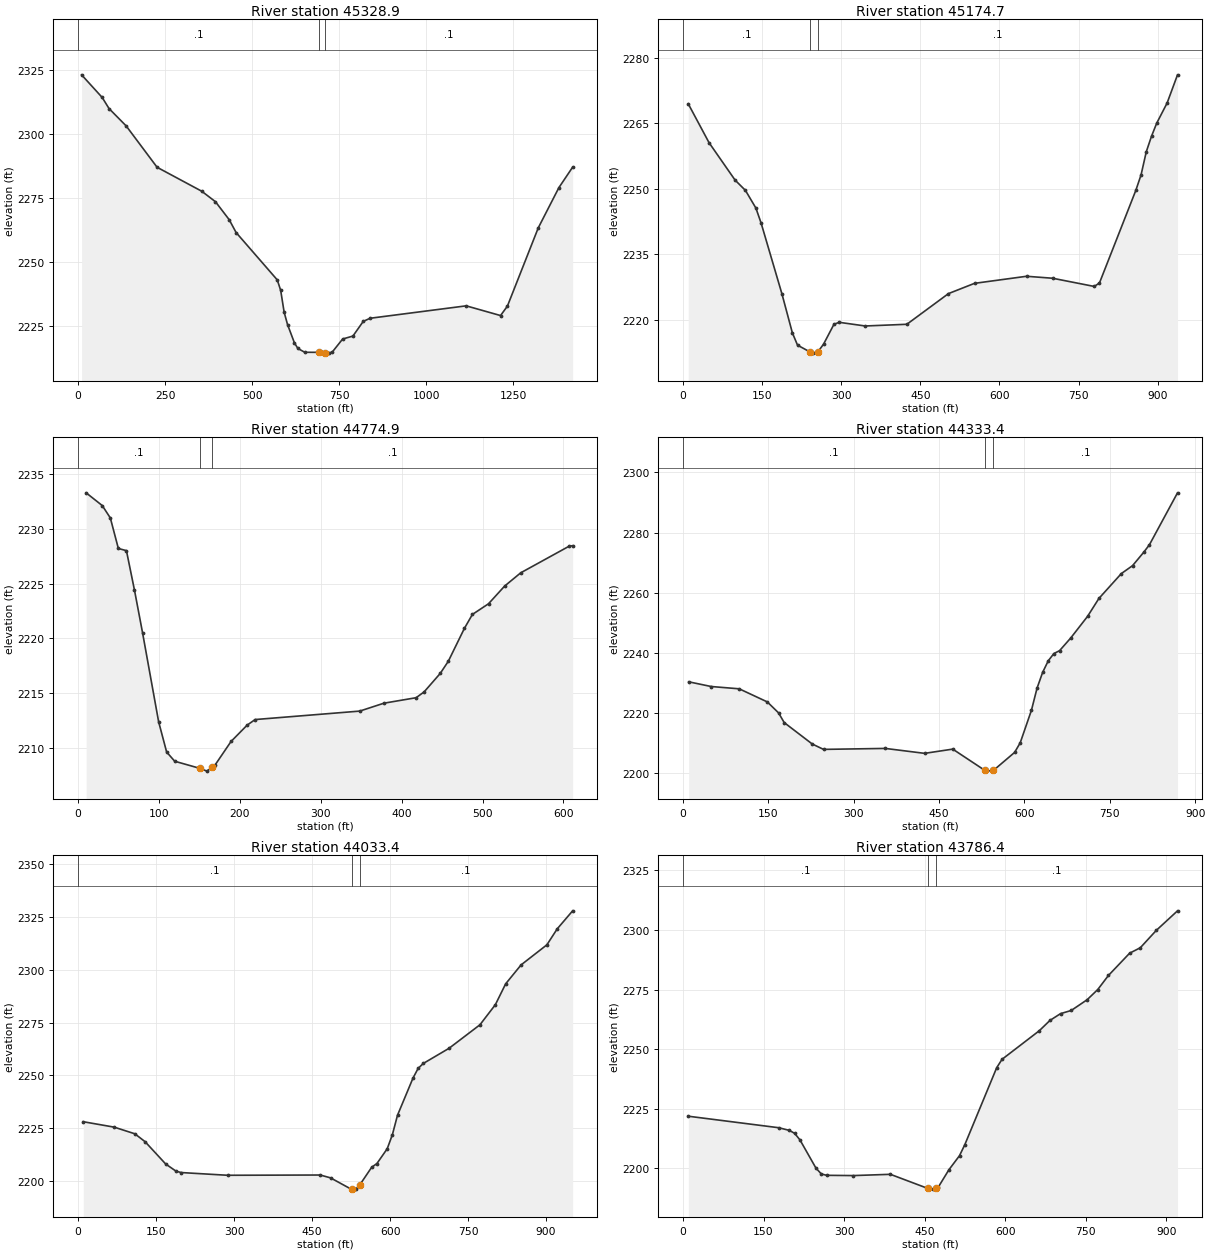
Type RM Length L Ch R = 1 ,45328.9 ,158.6,154.2,152.1
XS GIS Cut Line= 4
     2048708.549      298475.854     2049308.784      298593.818
     2049392.943      298564.392     2050045.747      298260.177
#Sta/Elev= 30
     9.9 2323.19    69.1 2314.33    88.8 2309.99   138.1 2303.19   226.9 2287.02
   355.2 2277.65   394.7 2273.54   434.1 2266.52   453.9  2261.5   572.3 2242.95
   582.1 2238.85     592 2230.33   601.9 2225.44   621.6 2218.31   631.5 2216.13
   651.3 2214.64   693.4 2214.62   708.4 2214.46   720.6 2214.31   730.5 2214.76
   760.1 2219.83   789.7 2220.99   819.3 2226.72     839 2227.95  1115.2 2232.81
  1213.9 2229.01  1233.6 2232.69  1322.4 2263.34  1381.6 2279.06  1421.1 2287.07
#Mann= 3 , 0 , 0
       0      .1       0   693.4    .045       0   708.4      .1       0
Bank Sta=693.4,708.4
XS Rating Curve= 0 ,0
Exp/Cntr=0.3,0.1

Type RM Length L Ch R = 1 ,45174.7 ,420,399.8,379.6
XS GIS Cut Line= 2
     2049236.238       298832.67     2050045.621      298359.386
#Sta/Elev= 30
     9.9 2269.49    49.3 2260.59    98.7 2252.01   118.4 2249.64   138.2 2245.59
     148 2242.19   187.5 2225.96   207.3 2217.02   217.1 2214.19   240.7 2212.63
   246.7 2212.36   255.7 2212.65   266.5 2214.42   286.2 2218.97   296.1 2219.42
   345.4 2218.58   424.4 2218.97   503.3    2226   552.7 2228.35   651.4 2229.97
   700.7 2229.52   779.7 2227.64   789.6 2228.43   858.6 2249.67   868.5 2253.21
   878.4 2258.51   888.3 2262.06   898.1 2265.04   917.9 2269.68   937.6 2276.13
#Mann= 3 , 0 , 0
       0      .1       0   240.7    .045       0   255.7      .1       0
Bank Sta=240.7,255.7
XS Rating Curve= 0 ,0
Exp/Cntr=0.3,0.1

Type RM Length L Ch R = 1 ,44774.9 ,423.8,441.4,459
XS GIS Cut Line= 3
     2049695.803      299137.903     2049784.973      298537.725
     2049789.097      298535.739
#Sta/Elev= 30
     9.9 2233.27    29.8 2232.11    39.8 2230.98    49.7  2228.2    59.7    2228
    69.6 2224.42    79.6 2220.53    99.5 2212.41   109.4 2209.65   119.4 2208.81
   150.6 2208.16   159.2 2207.91   165.6 2208.26   169.1 2208.45     189 2210.61
   208.9  2212.1   218.8 2212.61   348.1 2213.38     378  2214.1   417.8  2214.6
   427.7 2215.13   447.6 2216.81   457.6 2217.92   477.5 2220.92   487.4 2222.19
   507.3 2223.16   527.2 2224.77   547.1 2225.98   606.8  2228.4   611.3 2228.45
#Mann= 3 , 0 , 0
       0      .1       0   150.6    .045       0   165.6      .1       0
Bank Sta=150.6,165.6
XS Rating Curve= 0 ,0
Exp/Cntr=0.3,0.1

Type RM Length L Ch R = 1 ,44333.4 ,302.1,300,297.9
XS GIS Cut Line= 2
     2049781.543      299299.094     2050368.003      298657.761
#Sta/Elev= 30
     9.9 2230.29    49.4 2228.72    98.8 2227.95   148.1 2223.59   167.9 2219.94
   177.8 2216.71   227.1 2209.57   246.9 2207.78   355.5  2208.1   424.6 2206.46
     474 2207.87   530.5 2200.78   543.2 2200.54   545.5 2200.78   582.7 2206.77
   592.5 2209.94   612.3 2220.81   622.2  2228.2     632 2233.44   641.9  2237.3
   651.8 2239.71   661.7 2240.65   681.4 2244.89     711  2252.1   730.8 2258.03
   770.3 2266.33     790 2268.97   809.8 2273.47   819.7 2275.95     869 2293.22
#Mann= 3 , 0 , 0
       0      .1       0   530.5    .045       0   545.5      .1       0
Bank Sta=530.5,545.5
XS Rating Curve= 0 ,0
Exp/Cntr=0.3,0.1

Type RM Length L Ch R = 1 ,44033.4 ,247.3,247,246.8
XS GIS Cut Line= 2
     2049955.268      299463.816     2050648.513      298812.835
#Sta/Elev= 30
     9.9  2228.1    69.3 2225.54     109  2222.4   128.8 2218.65   168.4  2208.1
   188.2 2204.73   198.1 2204.07   287.3 2202.78   465.6  2202.9   485.4 2201.56
     525 2196.23   526.5 2196.24   534.9 2196.34   541.5 2198.19   564.6 2206.59
   574.6 2208.33   594.4 2215.32   604.3 2221.93   614.2 2231.17   643.9 2248.69
   653.8  2253.3   663.7 2255.64   713.2  2262.8   772.7 2273.93   802.4 2283.44
   822.2 2293.31   851.9 2302.26   901.5 2311.75   921.3 2319.28     951 2327.82
#Mann= 3 , 0 , 0
       0      .1       0   526.5    .045       0   541.5      .1       0
Bank Sta=526.5,541.5
XS Rating Curve= 0 ,0
Exp/Cntr=0.3,0.1

Type RM Length L Ch R = 1 ,43786.4 ,290.1,287.2,284.4
XS GIS Cut Line= 2
     2050108.943      299630.953     2050790.147       299011.25
#Sta/Elev= 30
     9.9 2221.79   178.2 2216.96     198 2215.85   207.9 2214.59   217.8 2211.84
   247.6 2199.99   257.5 2197.56   267.4 2196.97   316.9 2196.86   386.2 2197.39
   455.6 2191.49   465.4 2191.17   470.6  2191.6   475.3 2191.98   495.1 2199.28
   514.9 2205.22   524.8 2209.84   584.2 2242.19   594.1 2245.69   663.4 2257.68
   683.3 2262.02   703.1 2264.88   722.9  2266.2   752.6 2270.72   772.4 2275.01
   792.2  2280.9   831.8 2290.28   851.6 2292.55   881.3 2299.83   920.9 2308.06
#Mann= 3 , 0 , 0
       0      .1       0   455.6    .045       0   470.6      .1       0
Bank Sta=455.6,470.6
XS Rating Curve= 0 ,0
Exp/Cntr=0.3,0.1

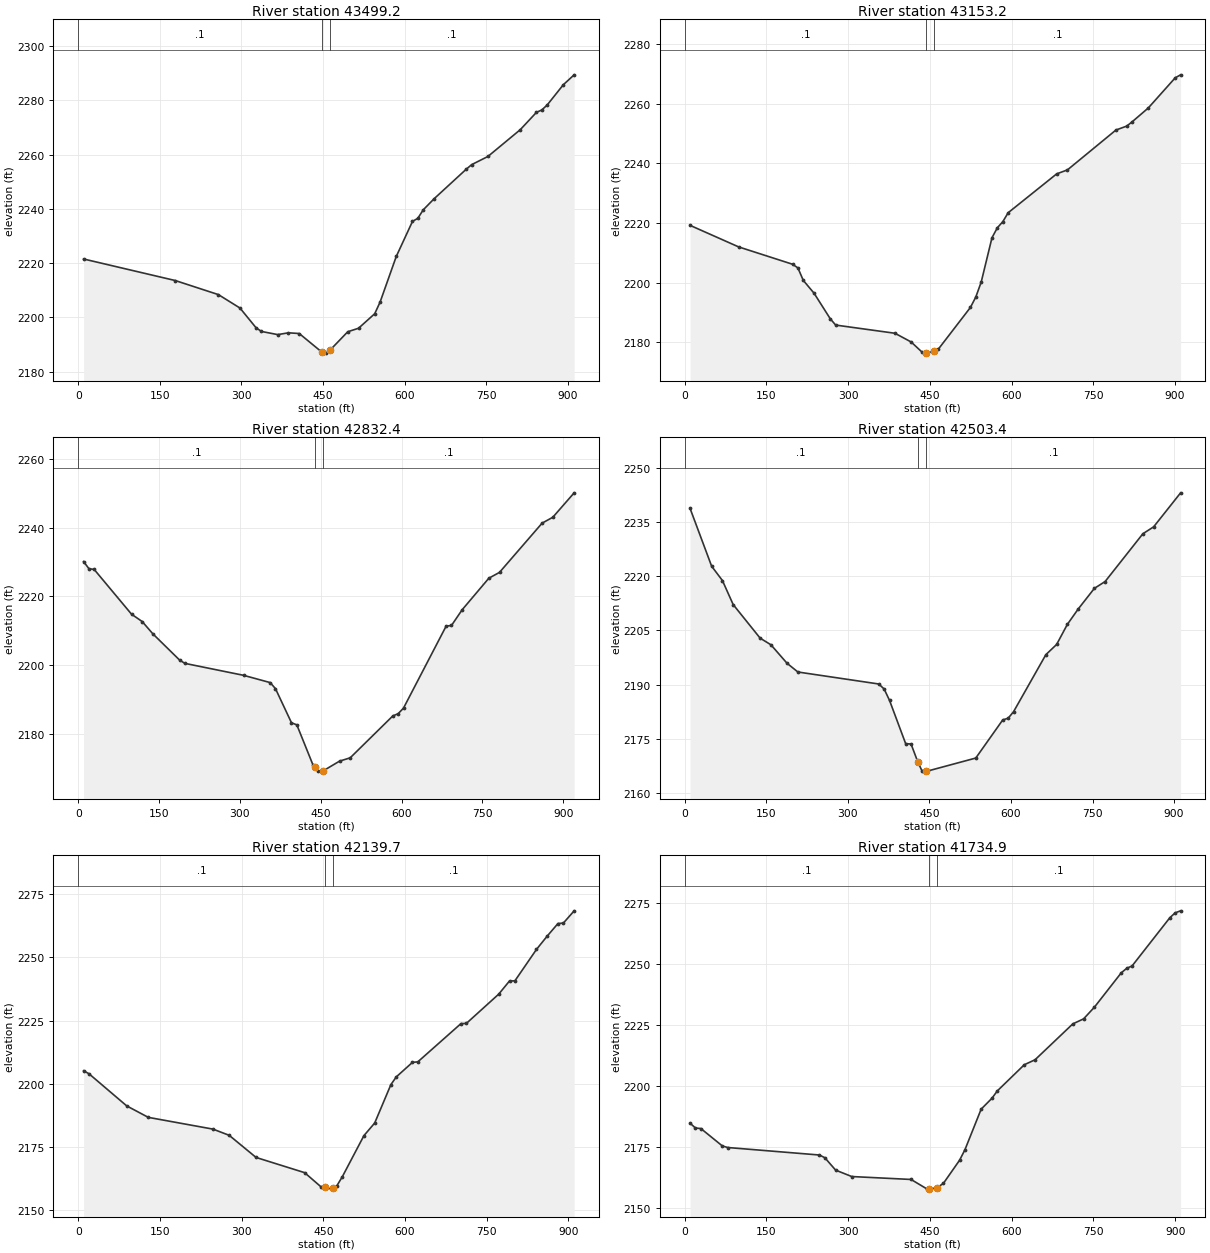
Type RM Length L Ch R = 1 ,43499.2 ,345.5,345.9,345.9
XS GIS Cut Line= 2
     2050335.544      299891.252     2050911.644      299184.331
#Sta/Elev= 30
     9.9  2221.5   178.4 2213.56   257.7 2208.37   297.4 2203.42   327.1 2196.12
     337 2194.78   366.8 2193.62   386.6 2194.28   406.4 2194.02   447.6 2187.23
     456 2186.79   462.6  2187.8   495.6 2194.67   515.4 2195.96   545.2 2201.32
   555.1 2205.62   584.8 2222.43   614.6 2235.35   624.5 2236.51   634.4 2239.62
   654.2 2243.68   713.7 2254.65   723.6 2256.31   753.3  2259.3   812.8 2269.18
   842.6 2275.58   852.5 2276.46   862.4 2278.31   892.1 2285.78   911.9 2289.41
#Mann= 3 , 0 , 0
       0      .1       0   447.6    .045       0   462.6      .1       0
Bank Sta=447.6,462.6
XS Rating Curve= 0 ,0
Exp/Cntr=0.3,0.1

Type RM Length L Ch R = 1 ,43153.2 ,328.4,320.8,313.8
XS GIS Cut Line= 3
     2050597.918      300100.497     2050893.107      299753.971
     2051178.468      299399.626
#Sta/Elev= 30
     9.9  2219.2      99 2211.97   197.9 2206.15   207.8 2204.92   217.7 2200.72
   237.5 2196.41   267.2 2187.84   277.1 2185.73   385.9 2182.98   415.6 2180.06
   435.4 2176.69   442.7 2176.41   445.3 2176.31   457.7 2177.09   465.1 2177.54
   524.4 2191.64   534.3 2195.14   544.2 2200.15     564 2215.05   573.9 2218.41
   583.8 2220.41   593.7 2223.44   682.7 2236.48   702.5 2237.82   791.5  2251.2
   811.3 2252.52   821.2 2253.95   850.8 2258.59   900.3 2268.73   910.2 2269.73
#Mann= 3 , 0 , 0
       0      .1       0   442.7    .045       0   457.7      .1       0
Bank Sta=442.7,457.7
XS Rating Curve= 0 ,0
Exp/Cntr=0.3,0.1

Type RM Length L Ch R = 1 ,42832.4 ,334.6,328.9,323.2
XS GIS Cut Line= 2
     2050967.027      300381.304     2051301.623      299524.235
#Sta/Elev= 30
     9.9 2230.11    19.8 2228.04    29.7 2227.79    98.9 2214.79   118.7 2212.65
   138.5 2209.07     188 2201.46   197.9 2200.48   306.7 2197.01   356.2 2194.89
     366 2193.12   395.7  2183.2   405.6  2182.6   435.3 2171.04   438.6 2170.41
   445.2 2169.15   453.6 2169.14   484.8 2172.04   504.6 2173.01   583.7  2185.2
   593.6 2185.85   603.5 2187.47   682.6 2211.32   692.5  2211.5   712.3 2216.07
   761.8 2225.25   781.6 2226.95   860.7 2241.28   880.5 2242.98   920.1 2250.09
#Mann= 3 , 0 , 0
       0      .1       0   438.6    .045       0   453.6      .1       0
Bank Sta=438.6,453.6
XS Rating Curve= 0 ,0
Exp/Cntr=0.3,0.1

Type RM Length L Ch R = 1 ,42503.4 ,365,363.7,362.5
XS GIS Cut Line= 2
     2051388.955      300497.009     2051500.728      299591.904
#Sta/Elev= 30
     9.9 2238.79    49.6 2222.77    69.4 2218.81    89.2 2212.15   138.8 2202.85
   158.6 2201.02   188.3 2195.89   208.2 2193.48   356.9 2190.16   366.8 2188.77
   376.7 2185.62   406.4 2173.63   416.3 2173.54   428.6 2168.61   436.2 2166.16
   443.6 2166.06   446.1 2166.03   535.3 2169.65   584.9 2180.21   594.8 2180.68
   604.7 2182.46   664.2 2198.28     684 2201.11   703.8 2206.69   723.6 2210.91
   753.4 2216.64   773.2 2218.54   842.6 2231.77   862.4 2233.68     912  2243.1
#Mann= 3 , 0 , 0
       0      .1       0   428.6    .045       0   443.6      .1       0
Bank Sta=428.6,443.6
XS Rating Curve= 0 ,0
Exp/Cntr=0.3,0.1

Type RM Length L Ch R = 1 ,42139.7 ,405.7,404.8,403.9
XS GIS Cut Line= 2
     2051760.772      300436.265     2051815.953      299527.298
#Sta/Elev= 30
     9.9 2205.11    19.8 2203.91    89.1 2191.17   128.7 2186.63   247.5 2181.97
   277.2 2179.52   326.6 2170.74   415.7 2164.72   445.4 2159.17   453.3 2158.94
   465.2 2158.19   468.3 2158.63   475.1 2159.59     485 2163.13   524.6 2179.39
   544.4  2184.4   574.1  2199.6     584 2202.67   613.7 2208.43   623.6 2208.64
   702.8 2223.79   712.7 2223.87   772.1 2235.47   791.9 2240.69   801.8 2240.74
   841.4 2253.19   861.1 2258.47   880.9 2263.46   890.8 2263.63   910.6 2268.49
#Mann= 3 , 0 , 0
       0      .1       0   453.3    .045       0   468.3      .1       0
Bank Sta=453.3,468.3
XS Rating Curve= 0 ,0
Exp/Cntr=0.3,0.1

Type RM Length L Ch R = 1 ,41734.9 ,320.9,324.8,328.6
XS GIS Cut Line= 3
     2052180.717      300443.103     2052192.308      299988.251
     2052203.899      299533.399
#Sta/Elev= 30
     9.9 2184.68    19.8 2182.68    29.7 2182.48    69.2 2175.31    79.1 2174.68
   247.3  2171.6   257.2 2170.48     277 2165.39   306.6 2162.76   415.4 2161.56
   445.1 2157.59   447.7 2157.65   462.7  2158.1   474.8 2159.98   504.5 2169.49
   514.3  2173.8     544 2190.44   563.8 2194.91   573.7 2197.94   623.2 2208.68
   642.9 2210.72   712.2 2225.46     732 2227.52   751.7 2232.29   801.2 2246.46
   811.1 2248.28     821 2249.27   890.2 2269.05   900.1 2271.08     910 2271.89
#Mann= 3 , 0 , 0
       0      .1       0   447.7    .045       0   462.7      .1       0
Bank Sta=447.7,462.7
XS Rating Curve= 0 ,0
Exp/Cntr=0.3,0.1

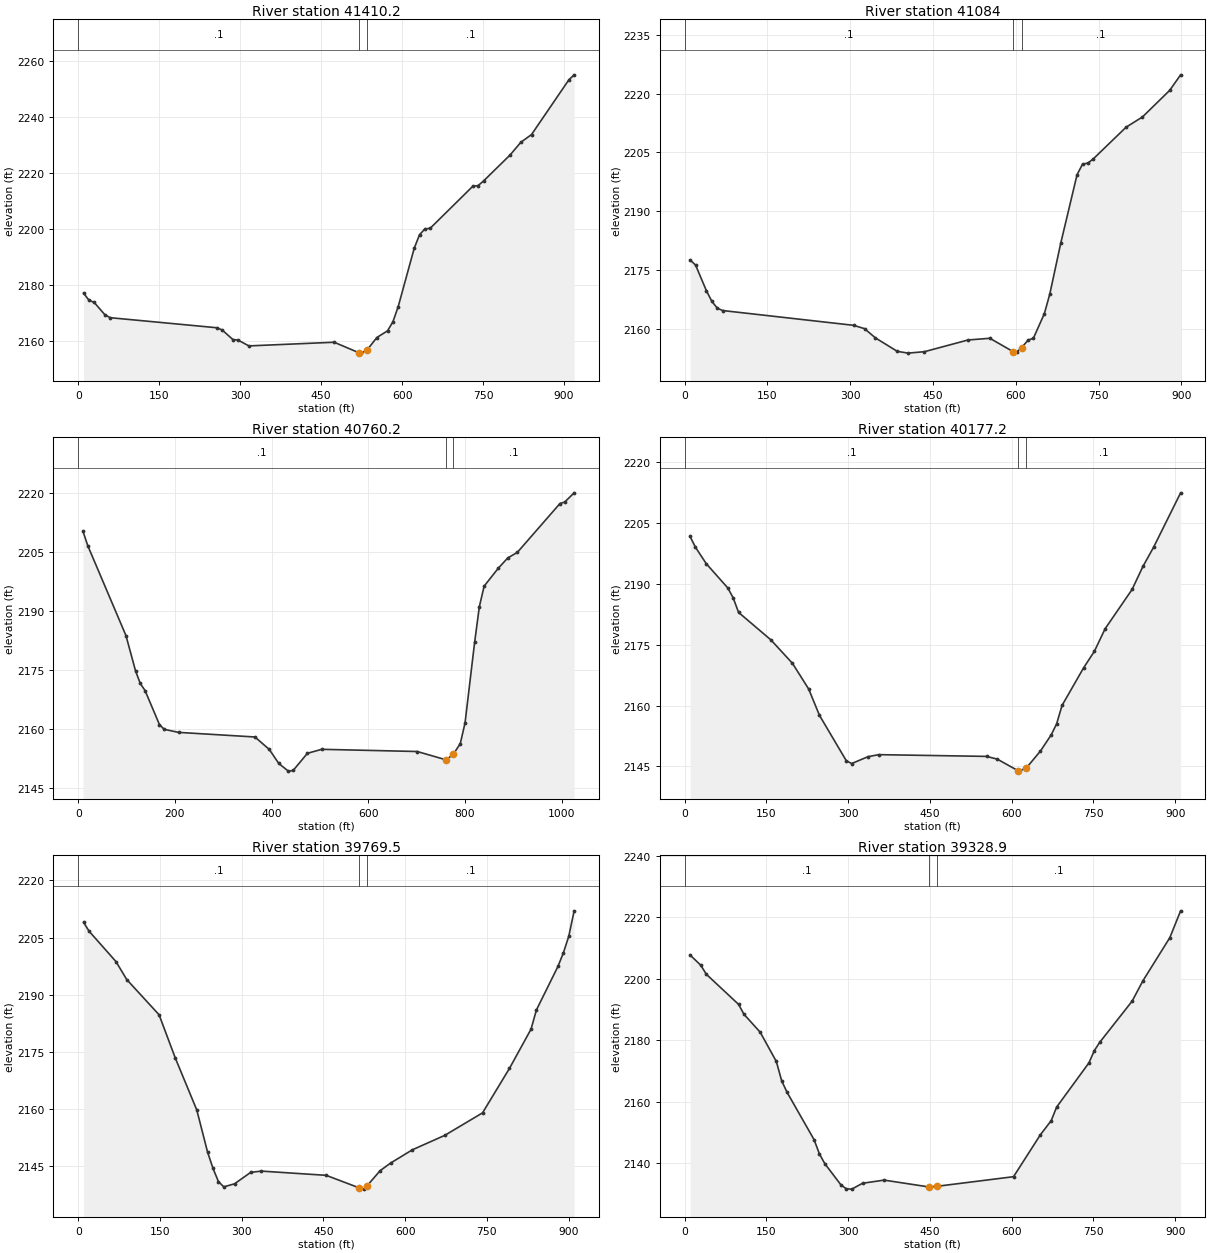
Type RM Length L Ch R = 1 ,41410.2 ,319.1,326.1,333.1
XS GIS Cut Line= 2
     2052413.923      300523.244     2052592.589      299621.971
#Sta/Elev= 30
     9.9 2177.05    19.8 2174.49    29.6 2173.69    49.4 2169.29    59.3 2168.23
   256.9 2164.64   266.8 2163.83   286.5 2160.43   296.4 2160.21   316.2 2158.15
   474.2 2159.46   519.7 2155.74   523.6 2155.57   534.7 2156.58   553.3 2161.15
     573 2163.53   582.9 2166.71   592.8 2172.17   622.4 2192.99   632.3 2197.88
   642.2 2199.94   652.1 2200.19   731.1 2215.22     741 2215.46   750.9 2217.09
   800.3 2226.42     820 2230.92   839.8 2233.68   908.9 2253.22   918.8 2255.03
#Mann= 3 , 0 , 0
       0      .1       0   519.7    .045       0   534.7      .1       0
Bank Sta=519.7,534.7
XS Rating Curve= 0 ,0
Exp/Cntr=0.3,0.1

Type RM Length L Ch R = 1 ,41084   ,316.8,323.8,330.8
XS GIS Cut Line= 2
     2052548.168      300598.058     2052977.715      299808.578
#Sta/Elev= 30
     9.9 2177.51    19.8 2176.19    39.5 2169.61    49.4 2166.91    59.3 2165.17
    69.1 2164.59   306.2 2160.82   325.9 2159.97   345.7 2157.61   385.2 2154.18
   404.9 2153.72   434.6 2154.09   513.6 2157.08   553.1 2157.51   595.5 2154.08
   602.5 2154.09   610.5 2155.11   622.2 2157.01   632.1 2157.55   651.9 2163.82
   661.7  2168.8   681.5 2181.76   711.1 2199.27     721 2201.96   730.9 2202.26
   740.7 2203.34     800 2211.41   829.6 2214.02     879 2220.81   898.8 2224.78
#Mann= 3 , 0 , 0
       0      .1       0   595.5    .045       0   610.5      .1       0
Bank Sta=595.5,610.5
XS Rating Curve= 0 ,0
Exp/Cntr=0.3,0.1

Type RM Length L Ch R = 1 ,40760.2 ,572.6,583,593.4
XS GIS Cut Line= 3
     2052552.886      300757.496     2053163.135      300180.537
     2053255.641      300019.007
#Sta/Elev= 30
     9.9 2210.18    19.8 2206.54    98.8 2183.72   118.6 2174.76   128.4 2171.56
   138.3 2169.77     168 2161.14   177.8 2159.93   207.5 2159.15   365.6 2157.98
   395.2 2154.83     415 2151.25   434.7 2149.31   444.6 2149.47   474.2 2153.84
   503.9 2154.85   701.5 2154.29   761.2 2152.17   776.2 2153.62   790.4 2156.29
   800.3 2161.57   820.1 2182.01   829.9 2191.09   839.8 2196.28   869.2 2200.85
   888.8 2203.45   908.4 2204.84   996.6 2217.25  1006.4 2217.63    1026 2219.97
#Mann= 3 , 0 , 0
       0      .1       0   761.2    .045       0   776.2      .1       0
Bank Sta=761.2,776.2
XS Rating Curve= 0 ,0
Exp/Cntr=0.3,0.1

Type RM Length L Ch R = 1 ,40177.2 ,408,407.7,407.4
XS GIS Cut Line= 2
     2052748.856      300942.458     2053618.852       300675.61
#Sta/Elev= 30
     9.9 2201.66    19.8 2199.01    39.6 2194.96    79.1 2188.98      89 2186.54
    98.9 2182.95   158.3 2176.17   197.8  2170.4   227.5 2164.08   247.3 2157.59
   296.7 2146.37   306.6 2145.71   336.3  2147.4   356.1  2147.9   553.9 2147.47
   573.7 2146.79   611.7 2143.95   613.3 2143.84   626.7 2144.59   652.8 2148.79
   672.6 2152.79   682.5 2155.49   692.4 2160.02     732  2169.3   751.7 2173.35
   771.5 2178.93     821 2188.62   840.8 2194.27   860.5 2199.03     910 2212.42
#Mann= 3 , 0 , 0
       0      .1       0   611.7    .045       0   626.7      .1       0
Bank Sta=611.7,626.7
XS Rating Curve= 0 ,0
Exp/Cntr=0.3,0.1

Type RM Length L Ch R = 1 ,39769.5 ,437.1,440.7,444.2
XS GIS Cut Line= 2
     2052888.995      301324.836     2053755.688      301047.429
#Sta/Elev= 30
     9.9 2208.98    19.8 2206.69    69.2 2198.71      89 2193.99   148.4 2184.73
     178 2173.44   217.6 2159.74   237.4 2148.68   247.3 2144.44   257.2 2140.99
   267.1 2139.59   286.8 2140.38   316.5 2143.39   336.3 2143.72     455 2142.61
   514.7 2139.37   524.2 2138.99   529.7 2139.81   553.9 2143.82   573.7 2145.88
   613.3 2149.32   672.6  2153.1   741.9    2159   791.3 2170.67   830.9 2180.97
   840.8 2186.01   880.3 2197.43   890.2 2200.97   900.1 2205.32     910 2212.01
#Mann= 3 , 0 , 0
       0      .1       0   514.7    .045       0   529.7      .1       0
Bank Sta=514.7,529.7
XS Rating Curve= 0 ,0
Exp/Cntr=0.3,0.1

Type RM Length L Ch R = 1 ,39328.9 ,281.7,280.1,278.5
XS GIS Cut Line= 2
     2052994.367      301673.007     2053893.363      301531.916
#Sta/Elev= 30
     9.9 2207.66    29.7  2204.3    39.6 2201.42    98.9 2191.61   108.8 2188.39
   138.5 2182.58   168.2 2173.04     178 2166.73   187.9 2163.02   237.4 2147.64
   247.3 2142.98   257.2 2139.81   286.8 2132.91   296.7 2131.64   306.6 2131.55
   326.4 2133.46     366 2134.48   447.5 2132.28   462.5 2132.46   603.4 2135.59
   652.8 2149.25   672.6 2153.83   682.5 2158.22   741.8 2172.61   751.7 2176.58
   761.6 2179.28     821 2192.66   840.8 2199.27   890.2  2213.3     910 2222.02
#Mann= 3 , 0 , 0
       0      .1       0   447.5    .045       0   462.5      .1       0
Bank Sta=447.5,462.5
XS Rating Curve= 0 ,0
Exp/Cntr=0.3,0.1

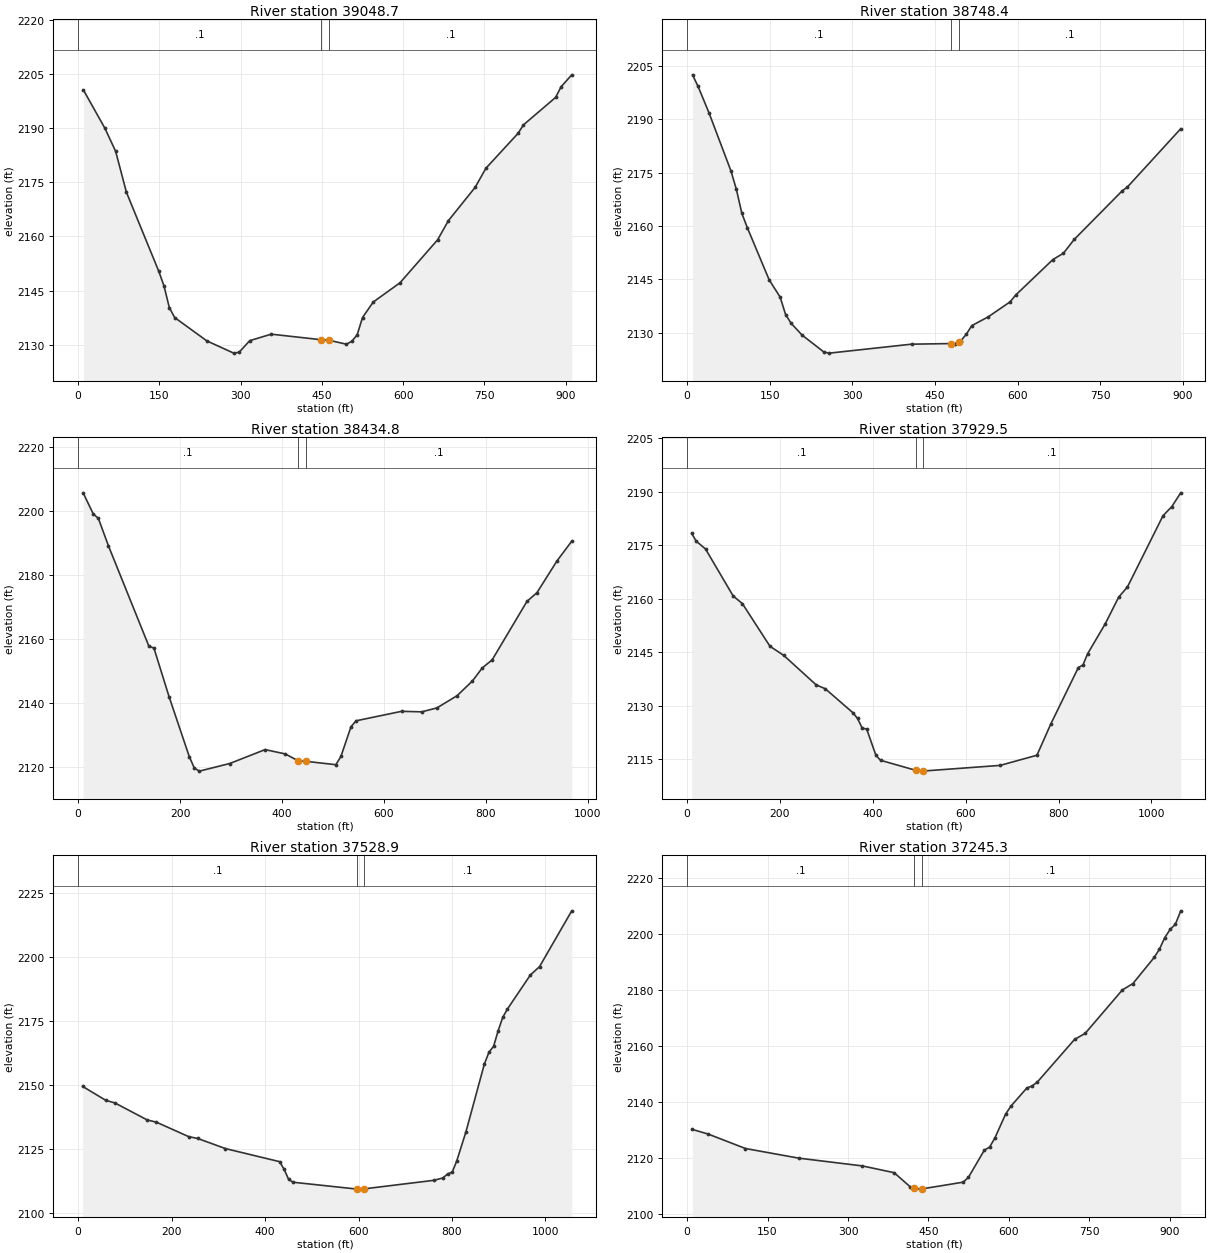
Type RM Length L Ch R = 1 ,39048.7 ,307.4,300.3,293.2
XS GIS Cut Line= 2
     2053078.785      301972.619     2053966.781      301767.246
#Sta/Elev= 30
     9.9  2200.5    49.5 2189.92    69.3 2183.54    89.2 2172.21   148.6 2150.45
   158.5 2146.32   168.4 2140.28   178.3 2137.51   237.8 2131.04   287.3 2127.66
   297.2  2127.9     317 2131.12   356.6 2132.91   447.8 2131.39   462.8 2131.24
   495.3 2130.13   505.3 2130.93   515.2 2132.72   525.1 2137.52   544.9 2141.81
   594.4 2147.15   663.8 2159.05   683.6 2164.33   733.1 2173.58   752.9 2178.85
   812.4 2188.54   822.3 2190.87   881.7 2198.48   891.6 2201.39   911.4 2204.72
#Mann= 3 , 0 , 0
       0      .1       0   447.8    .045       0   462.8      .1       0
Bank Sta=447.8,462.8
XS Rating Curve= 0 ,0
Exp/Cntr=0.3,0.1

Type RM Length L Ch R = 1 ,38748.4 ,322.8,313.7,304.6
XS GIS Cut Line= 3
     2053216.826       302392.35     2053729.028      302087.379
     2053936.945      301871.442
#Sta/Elev= 30
     9.9 2202.57    19.9 2199.32    39.7  2191.9    79.5 2175.57    89.4 2170.37
    99.4 2163.58   109.3 2159.55     149 2144.85   168.9    2140   178.8 2135.08
   188.8 2132.64   208.6 2129.32   248.4 2124.53   258.3 2124.23   407.3 2126.75
   478.4 2126.92   486.8 2126.91   493.4 2127.43   496.8  2127.7   506.7 2129.53
   516.6 2131.96   546.4 2134.43   586.2 2138.66   596.1 2140.53   663.8 2150.56
   683.1 2152.36   702.5 2156.22   789.5 2169.88   799.2    2171   895.9  2187.4
#Mann= 3 , 0 , 0
       0      .1       0   478.4    .045       0   493.4      .1       0
Bank Sta=478.4,493.4
XS Rating Curve= 0 ,0
Exp/Cntr=0.3,0.1

Type RM Length L Ch R = 1 ,38434.8 ,529.3,505.3,481.3
XS GIS Cut Line= 3
     2053533.657      302763.577      2053990.71      302139.413
     2054057.151      301956.032
#Sta/Elev= 30
     9.9 2205.57    29.8 2198.96    39.7 2197.62    59.5 2189.02   138.9 2157.65
   148.8 2157.06   178.5 2141.87   218.2 2123.12   228.1 2119.55     238  2118.6
   297.5 2120.98     367 2125.33   406.6 2123.97   432.1 2121.81   447.1 2121.66
   505.8 2120.61   515.7 2123.18   535.6  2132.5   545.5 2134.33   634.8 2137.29
   674.4 2137.13   704.2 2138.36   743.9  2142.2   773.6 2146.74   793.1 2150.84
   812.6 2153.39   880.9 2171.67   900.4 2174.35   939.4 2184.22   968.7 2190.46
#Mann= 3 , 0 , 0
       0      .1       0   432.1    .045       0   447.1      .1       0
Bank Sta=432.1,447.1
XS Rating Curve= 0 ,0
Exp/Cntr=0.3,0.1

Type RM Length L Ch R = 1 ,37929.5 ,400.9,400.6,400.8
XS GIS Cut Line= 4
     2054267.928      303007.172     2054281.413      302670.049
     2054079.412      302185.314     2054139.515      301993.874
#Sta/Elev= 30
     9.9 2178.33    19.8 2176.15    39.7 2173.98    99.2  2160.8   119.1 2158.65
   178.6 2146.67   208.4  2144.1   277.9 2135.86   297.7 2134.76   357.2 2128.03
   367.1 2126.43     377 2123.77   386.9 2123.42   406.8 2116.05   416.7 2114.69
     493 2111.86   505.8 2111.65     508 2111.67   674.3 2113.26   753.5 2116.11
   783.3 2124.86   842.7 2140.72   852.6 2141.42   862.5 2144.54   900.8 2153.03
   929.4 2160.43   948.5 2163.34    1025  2183.3  1044.1 2185.89  1063.2 2189.73
#Mann= 3 , 0 , 0
       0      .1       0     493    .045       0     508      .1       0
Bank Sta=493,508
XS Rating Curve= 0 ,0
Exp/Cntr=0.3,0.1

Type RM Length L Ch R = 1 ,37528.9 ,275.6,283.5,291
XS GIS Cut Line= 4
     2054603.426      302863.387     2054593.285       302508.95
     2054497.331      302279.144     2054332.633      301857.618
#Sta/Elev= 30
     9.8 2149.53    59.1 2144.12    78.8 2143.09   147.7 2136.47   167.4  2135.6
   236.4 2129.96   256.1 2129.22   315.2 2125.29   431.2 2120.18   440.8 2117.19
   450.4 2113.28   459.9 2112.16   596.1  2109.5   603.6 2109.47   611.1 2109.56
     761  2112.9   780.7 2113.84   790.5  2115.4   800.4 2116.06   810.2  2120.5
   829.9 2131.87   869.2 2158.25   879.1 2162.91   888.9 2165.13   898.8 2171.28
   908.6 2176.49   918.4 2179.68   967.6 2192.98   987.3 2196.27  1056.2 2218.03
#Mann= 3 , 0 , 0
       0      .1       0   596.1    .045       0   611.1      .1       0
Bank Sta=596.1,611.1
XS Rating Curve= 0 ,0
Exp/Cntr=0.3,0.1

Type RM Length L Ch R = 1 ,37245.3 ,331.5,333.1,334.6
XS GIS Cut Line= 2
     2054808.857      302649.073     2054716.626      301733.354
#Sta/Elev= 30
     9.9 2130.17    39.6 2128.49   108.9 2123.35   207.8 2119.92   326.6 2117.14
     386 2114.72   415.6 2109.74   422.4  2109.2   435.4 2108.84   437.4 2108.91
   514.6 2111.32   524.5 2113.02   554.2 2122.75   564.1 2123.86     574 2127.15
   593.8 2135.62   603.7 2138.47   633.4 2144.96   643.3 2145.68   653.2 2147.13
   722.4 2162.32   742.2 2164.48   811.5 2179.99   831.3  2182.3   870.9 2191.61
   880.8 2194.61   890.7  2198.7   900.6 2201.62   910.5  2203.5   920.4 2208.27
#Mann= 3 , 0 , 0
       0      .1       0   422.4    .045       0   437.4      .1       0
Bank Sta=422.4,437.4
XS Rating Curve= 0 ,0
Exp/Cntr=0.3,0.1

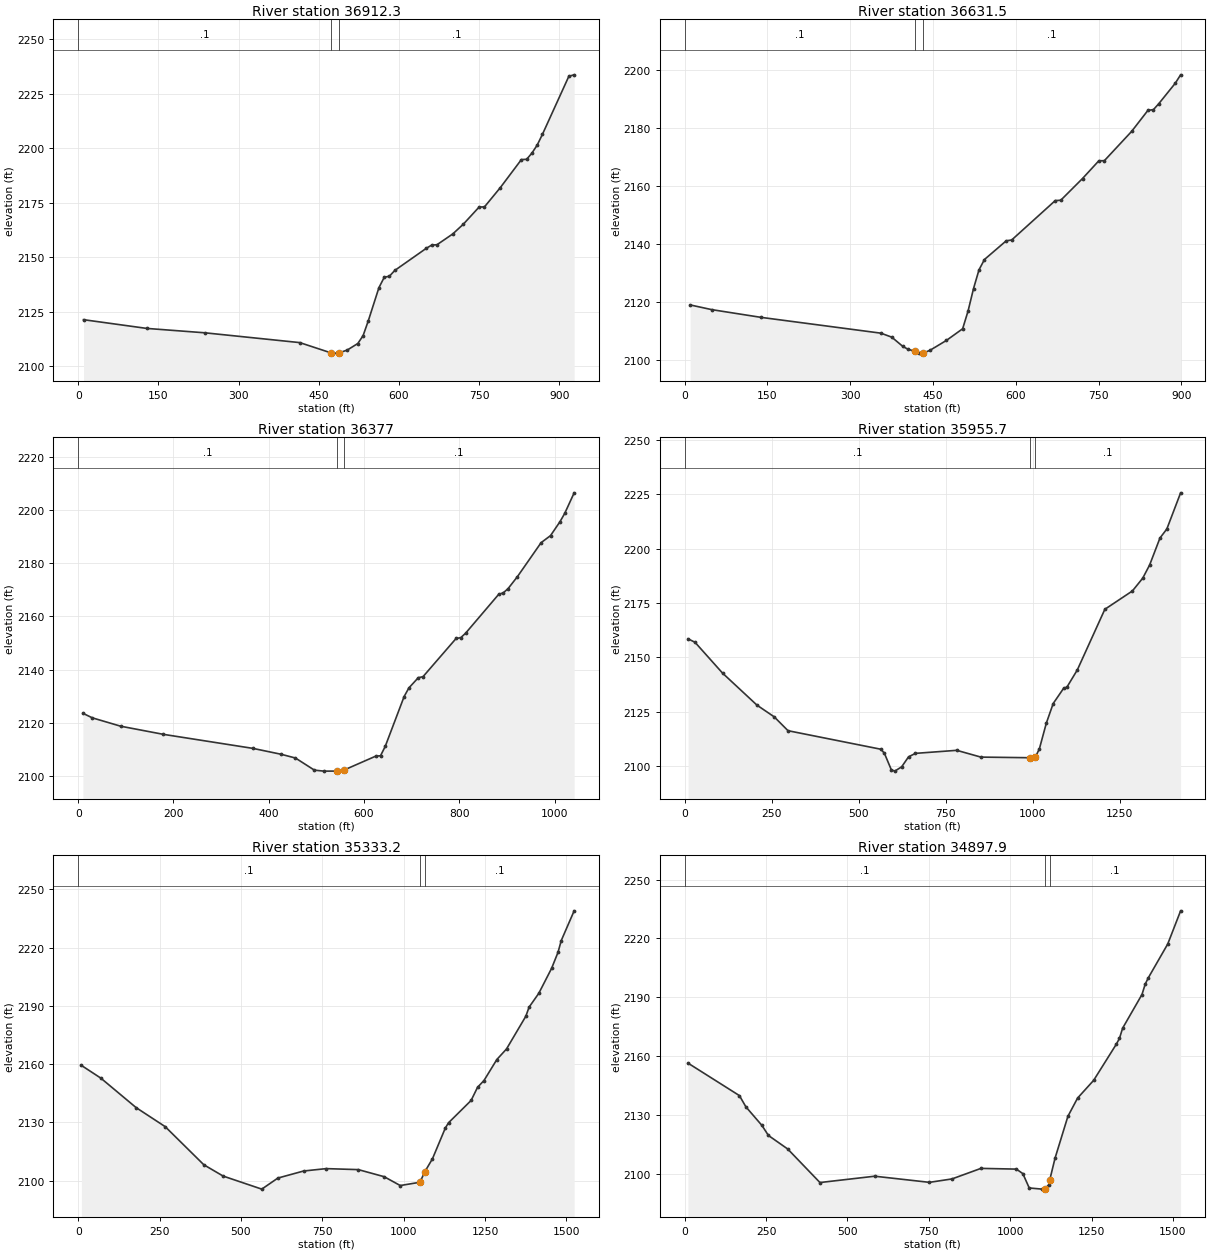
Type RM Length L Ch R = 1 ,36912.3 ,280.4,280.8,281.2
XS GIS Cut Line= 2
     2055041.022      302575.818     2055072.582      301648.587
#Sta/Elev= 30
     9.9 2121.41   128.3 2117.41   236.9  2115.4   414.5 2110.91   473.1 2106.19
   483.6 2106.09   488.1 2106.22   503.4 2107.51   523.1  2110.5     533 2114.12
   542.8 2120.98   562.6  2136.1   572.5 2140.81   582.3 2141.35   592.2 2143.96
   651.4 2154.14   661.3 2155.58   671.2 2155.74   700.8  2160.7   720.5 2165.16
   750.1 2173.03     760 2173.07   789.6 2181.88   829.1 2194.75   838.9 2194.87
   848.8 2197.72   858.7  2201.4   868.5 2206.33   917.9 2232.92   927.8 2233.57
#Mann= 3 , 0 , 0
       0      .1       0   473.1    .045       0   488.1      .1       0
Bank Sta=473.1,488.1
XS Rating Curve= 0 ,0
Exp/Cntr=0.3,0.1

Type RM Length L Ch R = 1 ,36631.5 ,252,254.4,256.8
XS GIS Cut Line= 2
     2055303.716      302575.867     2055353.607      301678.707
#Sta/Elev= 30
     9.9 2118.93    49.4 2117.29   138.2 2114.64   355.5 2109.18   375.2  2107.8
     395 2104.64   404.8  2103.6   417.5 2102.93   424.6 2102.29   432.5 2102.36
   444.3 2103.25     474 2106.65   503.6  2110.7   513.5 2116.89   523.3 2124.57
   533.2 2131.03   543.1 2134.61   582.6 2141.07   592.4 2141.34   671.4 2154.95
   681.3 2155.06   720.8 2162.57   750.4  2168.7   760.3 2168.71   809.7 2178.82
   839.3  2186.1   849.2 2186.33     859 2188.41   888.7 2195.43   898.5 2198.36
#Mann= 3 , 0 , 0
       0      .1       0   417.5    .045       0   432.5      .1       0
Bank Sta=417.5,432.5
XS Rating Curve= 0 ,0
Exp/Cntr=0.3,0.1

Type RM Length L Ch R = 1 ,36377   ,413.6,421.4,436.6
XS GIS Cut Line= 2
     2055493.598      302693.764     2055633.729       301662.13
#Sta/Elev= 30
     9.9 2123.51    29.7  2121.8    89.2 2118.65   178.5  2115.6   366.9  2110.3
   426.4 2108.07   456.1 2106.67   495.8 2102.11   515.6 2101.74   542.5 2101.76
   557.5 2102.11   624.7 2107.39   634.6 2107.52   644.5 2111.05   684.2 2129.83
   694.1 2133.06   713.9 2136.92   723.8  2137.3   793.2 2151.68   803.1    2152
   813.1 2153.65   882.5 2168.27   892.4 2168.89   902.3 2170.44   922.1 2174.99
   971.7 2187.76   991.5 2190.42  1011.4 2195.67  1021.3 2198.79  1041.1 2206.53
#Mann= 3 , 0 , 0
       0      .1       0   542.5    .045       0   557.5      .1       0
Bank Sta=542.5,557.5
XS Rating Curve= 0 ,0
Exp/Cntr=0.3,0.1

Type RM Length L Ch R = 1 ,35955.7 ,610.2,622.5,634.9
XS GIS Cut Line= 2
     2055529.538      302968.757     2056105.709      301665.512
#Sta/Elev= 30
     9.9  2158.5    29.7 2156.93   108.8 2142.73   207.8 2127.97   257.3 2122.58
   296.9 2116.21     564 2107.66   573.9 2105.78   593.7 2098.21   603.6 2097.59
   623.4 2099.57   643.2 2104.17     663 2105.77   781.7 2107.17     851 2104.05
   992.7 2103.76  1007.7 2104.07  1019.2 2107.92    1039 2119.65  1058.8 2128.73
  1088.5 2135.68  1098.4 2136.32  1128.1  2144.2  1207.2 2172.12  1286.4 2180.57
  1316.1 2186.47  1335.9 2192.54  1365.6 2204.96  1385.3  2209.1  1424.9 2225.76
#Mann= 3 , 0 , 0
       0      .1       0   992.7    .045       0  1007.7      .1       0
Bank Sta=992.7,1007.7
XS Rating Curve= 0 ,0
Exp/Cntr=0.3,0.1

Type RM Length L Ch R = 1 ,35333.2 ,426.5,435.2,443.9
XS GIS Cut Line= 2
     2055547.287      303003.036     2056809.633      302149.552
#Sta/Elev= 30
     9.9 2159.36    69.3 2152.85   178.1 2137.62   267.2 2127.85   385.9 2108.22
   445.3 2102.39     564 2095.67   613.5 2101.37   692.6    2105   761.9 2106.23
   860.8 2105.71     940 2102.07   989.5 2097.52    1050 2099.21    1065 2104.64
  1088.4 2111.28    1128 2127.14  1137.9 2129.85  1207.2 2141.33    1227  2148.1
  1246.7 2151.58  1286.3 2162.41    1316 2167.85  1375.4 2184.71  1385.3 2189.37
    1415 2196.45  1454.5 2209.35  1474.3 2217.64  1484.2 2223.68  1523.8 2238.97
#Mann= 3 , 0 , 0
       0      .1       0    1050    .045       0    1065      .1       0
Bank Sta=1050,1065
XS Rating Curve= 0 ,0
Exp/Cntr=0.3,0.1

Type RM Length L Ch R = 1 ,34897.9 ,557.6,572.4,587.3
XS GIS Cut Line= 2
     2055580.825      302999.801     2057070.374       302678.56
#Sta/Elev= 30
     9.9  2156.4   168.2  2139.8     188 2134.09   237.5 2124.56   257.3 2119.47
   316.6 2112.57   415.6 2095.46   583.8 2098.69     752 2095.56   821.3  2097.3
   910.3 2102.68  1019.2 2102.31    1039 2100.01  1058.7 2092.69  1098.3  2092.1
  1106.5 2092.32  1118.1  2094.2  1121.5 2096.64  1137.9 2107.86  1177.5 2129.25
  1207.2 2138.54  1256.6 2147.59  1325.9 2165.93  1335.8 2168.95  1345.7 2174.22
  1405.1 2191.37    1415 2196.66  1424.8 2199.96  1484.2 2217.12  1523.8 2234.05
#Mann= 3 , 0 , 0
       0      .1       0  1106.5    .045       0  1121.5      .1       0
Bank Sta=1106.5,1121.5
XS Rating Curve= 0 ,0
Exp/Cntr=0.3,0.1