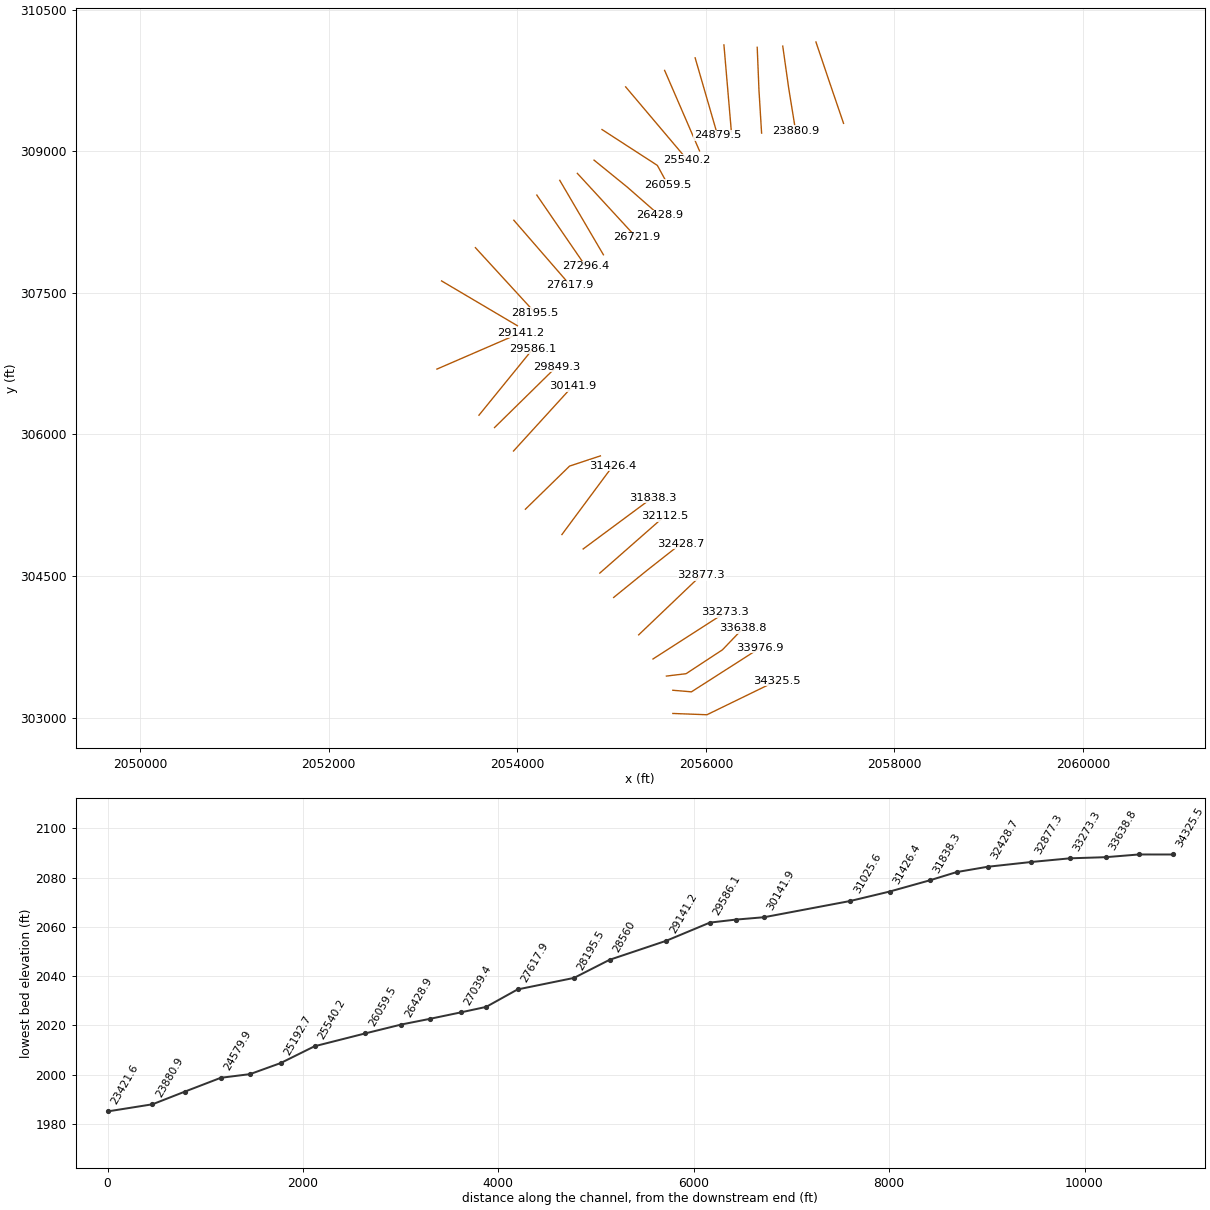
HEC-RAS study ABRMCRK.prj: ABRMCRK

--- ABRMCRK.g01 (geometry) --- (continued)

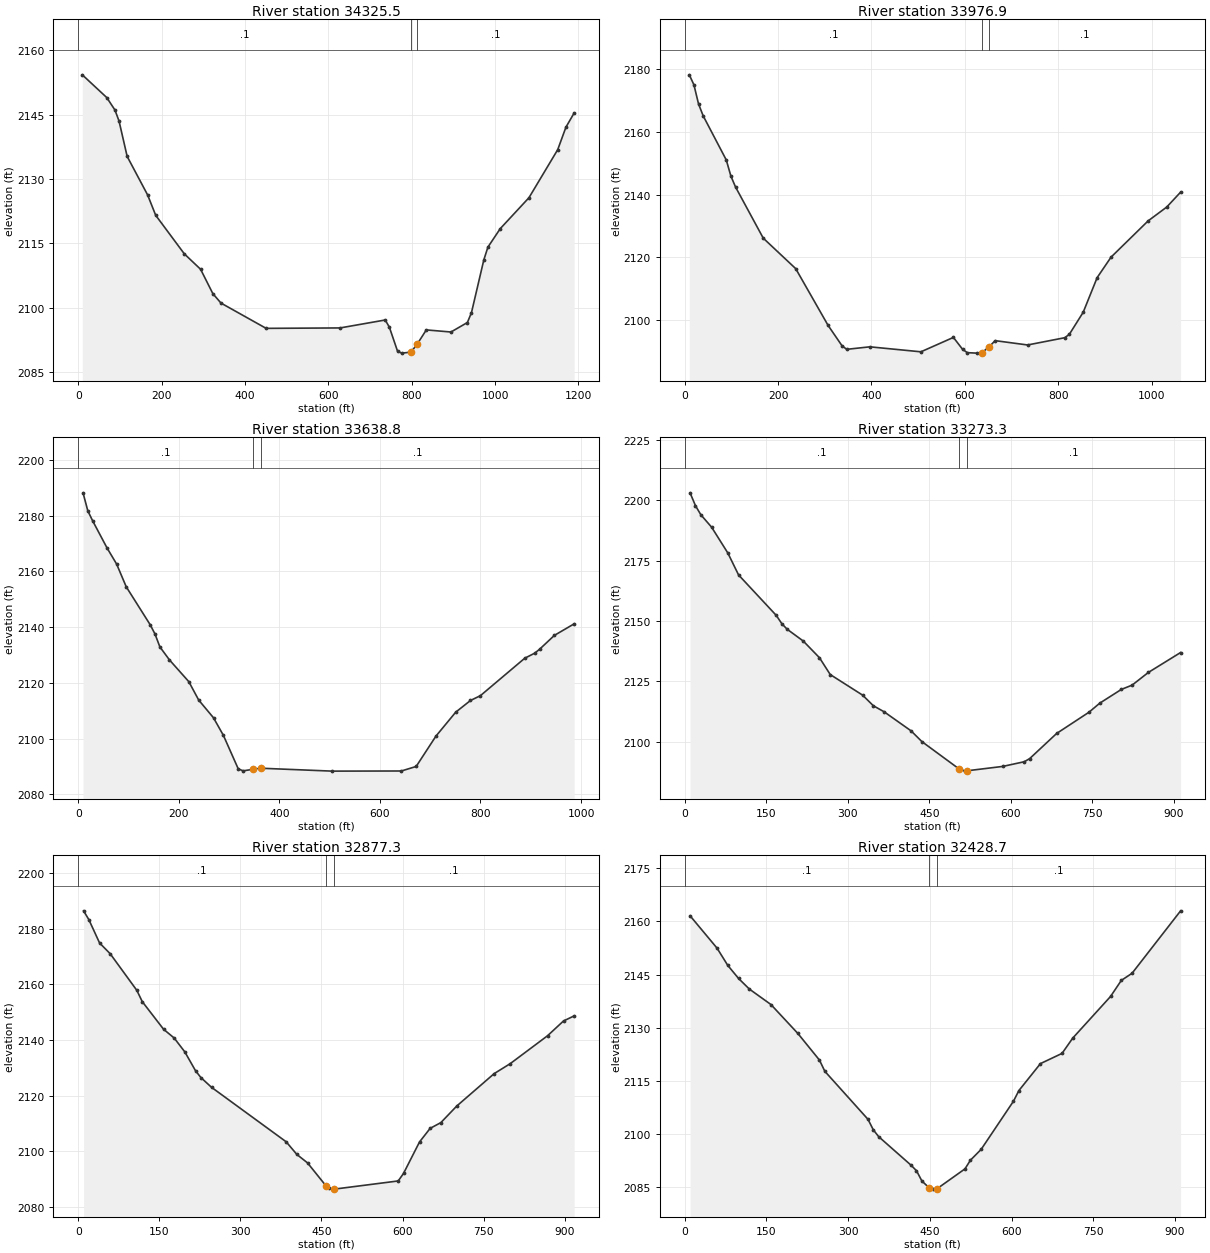
Type RM Length L Ch R = 1 ,34325.5 ,345.8,348.6,351.4
XS GIS Cut Line= 3
     2055649.697      303043.999     2056011.544      303030.345
     2056755.719      303392.192
#Sta/Elev= 30
     9.8 2154.27    68.5 2148.97    88.1 2146.07    97.9 2143.51   117.4 2135.26
   166.4  2126.3   185.9 2121.54   254.5 2112.56   293.6 2108.96     323 2103.28
   342.5 2101.09   450.8  2095.2   628.1  2095.3   736.4 2097.15   746.3 2095.49
     766 2089.87   775.8 2089.43     798 2089.65     813 2091.51     835 2094.84
   894.1 2094.35   933.5 2096.56   943.3 2098.86   972.9 2111.14   982.7 2114.12
  1012.3 2118.43  1081.2 2125.64  1150.2 2136.84  1169.9 2142.07  1189.6 2145.39
#Mann= 3 , 0 , 0
       0      .1       0     798    .045       0     813      .1       0
Bank Sta=798,813
XS Rating Curve= 0 ,0
Exp/Cntr=0.3,0.1

Type RM Length L Ch R = 1 ,33976.9 ,337.9,338.1,338.2
XS GIS Cut Line= 3
     2055649.697      303289.782     2055847.032      303273.109
     2056575.232      303738.672
#Sta/Elev= 30
     9.9 2178.16    19.8 2174.97    29.7 2168.87    39.6 2165.09    89.1 2151.02
      99 2145.87   108.9 2142.41   168.3 2126.09   237.8 2116.38   307.3 2098.25
   337.1 2091.77   347.1 2090.65   396.7 2091.45     506 2089.86   575.6 2094.45
   595.4 2090.63   605.4 2089.59   625.2 2089.44   636.9 2089.61   651.9 2091.43
     665 2093.42   734.5 2092.04     814 2094.35   823.9 2095.42   853.7 2102.49
   883.5 2113.51   913.3 2120.04   992.8 2131.61  1032.5    2136  1062.3 2140.76
#Mann= 3 , 0 , 0
       0      .1       0   636.9    .045       0   651.9      .1       0
Bank Sta=636.9,651.9
XS Rating Curve= 0 ,0
Exp/Cntr=0.3,0.1

Type RM Length L Ch R = 1 ,33638.8 ,366.1,365.5,364.9
XS GIS Cut Line= 4
     2055581.424      303439.983     2055790.049      303465.067
     2056176.285      303718.552     2056393.872      303945.203
#Sta/Elev= 30
     9.6 2188.18    19.1 2181.71    28.7 2178.14    57.3 2168.41    76.4 2162.62
    95.5 2154.47   143.3 2140.81   152.8 2137.49   162.4 2132.91   181.5 2128.23
     220 2120.43   239.6 2113.84   269.1 2107.46   288.8 2101.14   318.3 2089.14
   328.1 2088.44   348.4 2089.01   363.4 2089.38     505 2088.34   642.6 2088.39
   672.1 2090.01   711.4 2100.89   750.7 2109.48   780.1 2113.68   799.8  2115.4
   888.1 2128.85   907.8 2130.65   917.6 2132.07     947 2137.04   986.3 2141.18
#Mann= 3 , 0 , 0
       0      .1       0   348.4    .045       0   363.4      .1       0
Bank Sta=348.4,363.4
XS Rating Curve= 0 ,0
Exp/Cntr=0.3,0.1

Type RM Length L Ch R = 1 ,33273.3 ,391.7,396.1,400.4
XS GIS Cut Line= 2
     2055439.325      303621.049     2056206.729      304114.071
#Sta/Elev= 30
     9.9 2203.03    19.8 2197.73    29.7 2193.96    49.6 2188.79    79.3 2178.16
    99.1 2169.06   168.5  2152.3   178.5 2148.94   188.4  2146.6   218.1  2141.7
   247.9  2134.8   267.7 2127.84   327.2 2119.33     347 2114.93   366.8 2112.43
   416.4 2104.54   436.2 2100.11   503.8 2088.93   515.6 2087.88   518.8 2088.01
     585 2089.83   624.6 2091.77   634.5 2093.06   684.1 2103.47   743.6 2112.26
   763.4    2116   803.1 2121.69   822.9 2123.46   852.6 2128.69   912.1 2136.96
#Mann= 3 , 0 , 0
       0      .1       0   503.8    .045       0   518.8      .1       0
Bank Sta=503.8,518.8
XS Rating Curve= 0 ,0
Exp/Cntr=0.3,0.1

Type RM Length L Ch R = 1 ,32877.3 ,450.2,448.5,446.5
XS GIS Cut Line= 2
     2055287.617      303876.679     2055951.718      304509.789
#Sta/Elev= 30
     9.9 2186.39    19.7 2183.22    39.5 2174.85    59.2 2170.96   108.5  2157.8
   118.4 2153.79   157.9 2143.84   177.6 2140.67   197.3 2135.68     217 2128.94
   226.9 2126.49   246.6 2122.98   384.8 2103.39   404.5 2098.85   424.2 2095.83
   458.8 2087.47   463.7 2086.63   473.6 2086.39   473.8 2086.39     592 2089.33
   601.8 2092.02   631.4 2103.33   651.1 2108.23   670.9 2110.29   700.5 2116.28
   769.5 2127.89   799.1 2131.46   868.2 2141.49   897.8 2146.81   917.5 2148.64
#Mann= 3 , 0 , 0
       0      .1       0   458.8    .045       0   473.8      .1       0
Bank Sta=458.8,473.8
XS Rating Curve= 0 ,0
Exp/Cntr=0.3,0.1

Type RM Length L Ch R = 1 ,32428.7 ,315.5,316.2,317.3
XS GIS Cut Line= 3
     2055022.232      304272.863     2055375.659      304559.526
     2055733.447      304840.599
#Sta/Elev= 30
     9.9 2161.57    59.4 2152.44    79.1 2147.57    98.9 2143.88   118.7 2140.89
   158.3 2136.53   207.7 2128.37   247.3 2120.86   257.2 2117.69   336.4 2104.14
   346.2 2101.16   356.1 2099.23   415.5 2091.18   425.4 2089.63   435.3 2086.74
   448.5 2084.83   455.1 2084.44   463.5 2084.59   514.4 2090.16   524.3 2092.59
   544.1 2095.67   603.4 2109.26   613.3 2112.25   652.9 2119.86   692.5 2122.74
   712.2 2127.07   781.5  2138.8   801.3 2143.34     821 2145.35   910.1 2162.97
#Mann= 3 , 0 , 0
       0      .1       0   448.5    .045       0   463.5      .1       0
Bank Sta=448.5,463.5
XS Rating Curve= 0 ,0
Exp/Cntr=0.3,0.1

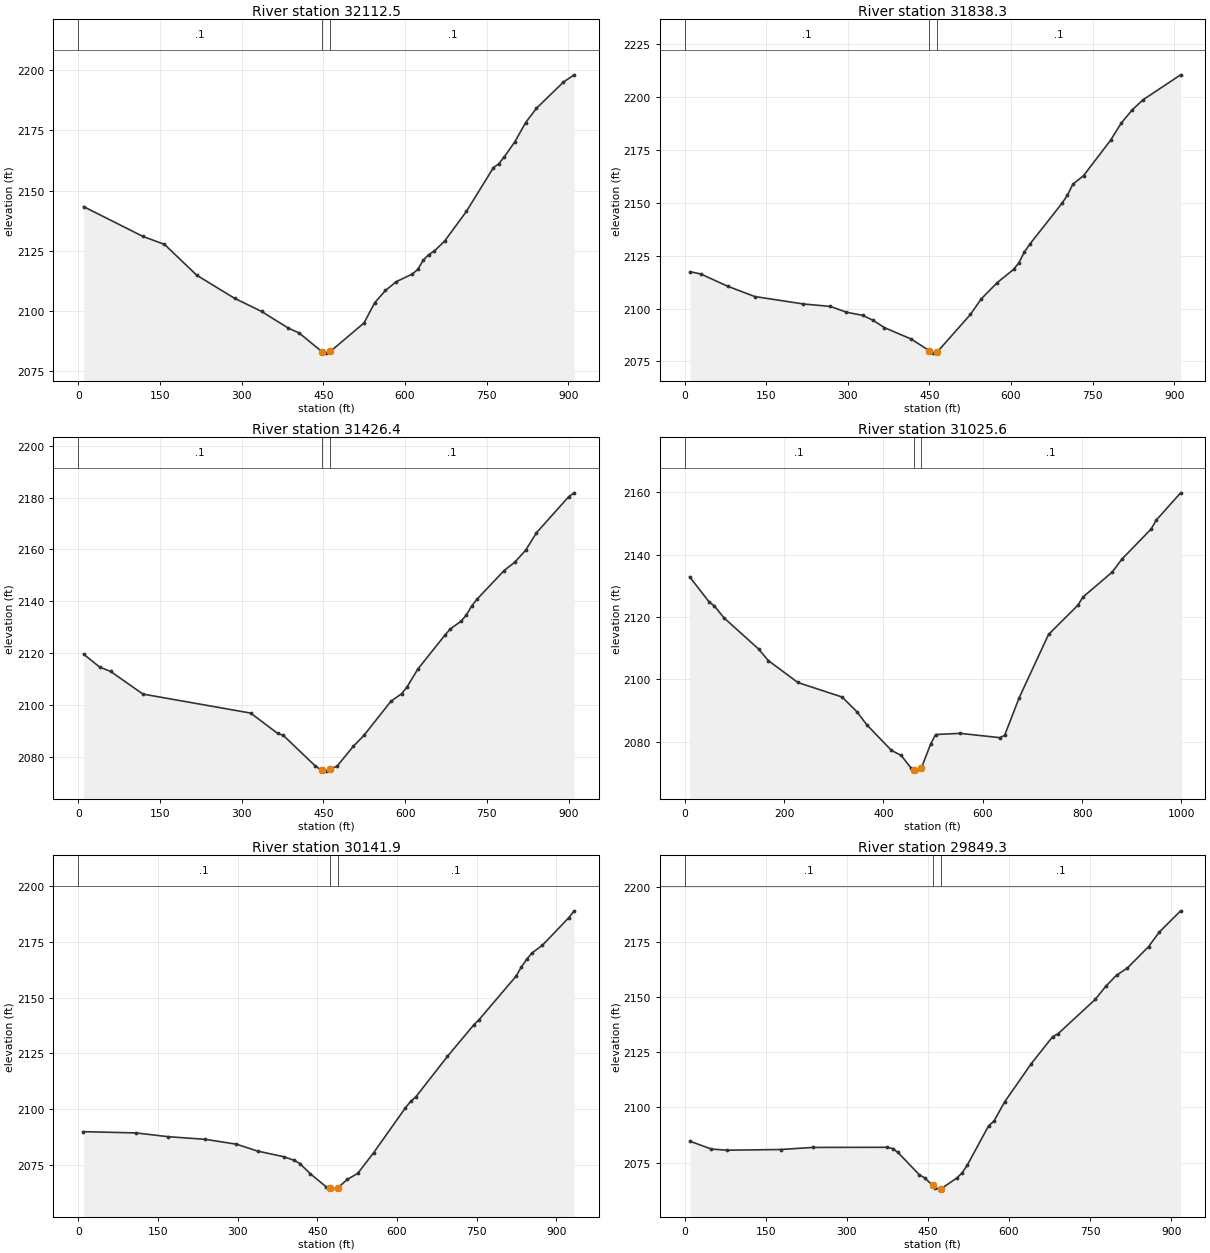
Type RM Length L Ch R = 1 ,32112.5 ,276.1,274.2,272.3
XS GIS Cut Line= 2
     2054875.338      304530.845     2055559.578      305131.607
#Sta/Elev= 30
     9.9 2143.29   118.8 2130.89   158.4 2127.57   217.7 2114.72     287 2105.13
   336.5 2099.66     386 2092.68   405.8 2090.65     448 2082.78   455.3 2082.29
     463 2083.02   524.6 2094.82   544.4 2103.31   564.1 2108.39   583.9 2112.03
   613.6 2115.26   623.5 2117.18   633.4 2120.98   643.3 2123.31   653.2 2124.67
     673 2129.03   712.6 2141.28   762.1 2159.46     772 2161.14   781.9 2163.91
   801.7 2170.32   821.5 2178.32   841.3 2184.25   890.8 2195.16   910.5 2198.18
#Mann= 3 , 0 , 0
       0      .1       0     448    .045       0     463      .1       0
Bank Sta=448,463
XS Rating Curve= 0 ,0
Exp/Cntr=0.3,0.1

Type RM Length L Ch R = 1 ,31838.3 ,405.1,411.9,418.6
XS GIS Cut Line= 2
     2054699.158      304786.577     2055432.185      305329.081
#Sta/Elev= 30
     9.9 2117.41    29.7 2116.32    79.3 2110.52   128.9 2105.67   218.1 2102.17
   267.6 2101.01   297.4 2098.29   327.1 2096.79   346.9  2094.4   366.8 2091.05
   416.3 2085.62   449.8 2080.11     456 2078.95   464.8 2079.62   525.4 2097.21
   545.2 2104.53   574.9 2112.29   604.7 2118.47   614.6 2121.67   624.5 2126.66
   634.4 2130.34   693.9 2149.76   703.8 2153.57   713.7 2158.68   733.5  2162.8
   783.1 2179.48   802.9 2187.66   822.7 2193.77   842.6 2198.56   911.9 2210.38
#Mann= 3 , 0 , 0
       0      .1       0   449.8    .045       0   464.8      .1       0
Bank Sta=449.8,464.8
XS Rating Curve= 0 ,0
Exp/Cntr=0.3,0.1

Type RM Length L Ch R = 1 ,31426.4 ,405,400.9,396.8
XS GIS Cut Line= 3
     2054473.379       304939.04     2054744.624       305304.35
     2055015.869      305669.659
#Sta/Elev= 30
     9.9 2119.55    39.6 2114.52    59.3 2112.91   118.7 2104.14   316.5 2096.79
     366 2088.93   375.9 2088.26   435.2 2076.35   446.9 2074.71     455 2074.38
   461.9 2075.16   474.8 2076.25   504.5  2083.9   524.2 2088.16   573.7 2101.34
   593.5 2104.29   603.4 2106.88   623.2  2113.8   672.6 2126.82   682.5 2129.24
   702.3 2132.25   712.2 2134.62   722.1  2138.2     732 2140.83   781.4 2151.82
   801.2 2155.09     821 2159.68   840.8 2166.42   900.1 2180.38     910 2181.85
#Mann= 3 , 0 , 0
       0      .1       0   446.9    .045       0   461.9      .1       0
Bank Sta=446.9,461.9
XS Rating Curve= 0 ,0
Exp/Cntr=0.3,0.1

Type RM Length L Ch R = 1 ,31025.6 ,881.5,883.6,885.7
XS GIS Cut Line= 3
     2054086.581      305207.817     2054554.642        305664.3
     2054881.675      305772.444
#Sta/Elev= 30
     9.9  2132.9    49.5 2124.76    59.4  2123.6    79.2 2119.71   148.6 2109.76
   168.4 2106.01   227.8 2098.99     317 2094.32   346.7 2089.61   366.5 2085.45
   416.1 2077.23   435.9 2075.59   455.7 2071.55   461.2    2071   465.6 2070.57
   476.2 2071.48   495.3 2079.33   505.2 2082.31   554.7 2082.68     634 2081.31
   643.9    2082   673.5 2094.16   732.5 2114.42   791.6 2123.78   801.4 2126.34
   860.5 2134.38   880.2 2138.56   939.2 2148.25     949 2151.01   998.3 2159.81
#Mann= 3 , 0 , 0
       0      .1       0   461.2    .045       0   476.2      .1       0
Bank Sta=461.2,476.2
XS Rating Curve= 0 ,0
Exp/Cntr=0.3,0.1

Type RM Length L Ch R = 1 ,30141.9 ,293.9,292.7,291.4
XS GIS Cut Line= 2
     2053960.279      305824.026     2054589.558      306513.476
#Sta/Elev= 30
     9.9  2089.8   109.2 2089.22   168.8 2087.54   238.3 2086.37   297.9 2084.16
   337.6 2081.06   387.3 2078.51   407.1 2076.86   417.1 2075.48   436.9 2070.87
   466.7 2065.02   473.9 2064.26   476.7 2063.96   488.9 2064.62   506.4 2068.29
   526.3 2071.08   556.1 2080.34   615.7 2100.44   625.6 2103.36   635.5 2105.44
   695.1 2123.65   744.8 2137.86   754.7 2140.18   824.2 2159.69   834.1 2163.81
   844.1 2167.24     854 2170.09   873.9 2173.61   923.5 2186.01   933.5 2189.06
#Mann= 3 , 0 , 0
       0      .1       0   473.9    .045       0   488.9      .1       0
Bank Sta=473.9,488.9
XS Rating Curve= 0 ,0
Exp/Cntr=0.3,0.1

Type RM Length L Ch R = 1 ,29849.3 ,260.7,263.2,265.7
XS GIS Cut Line= 2
     2053759.197      306072.681     2054414.075      306715.275
#Sta/Elev= 30
     9.9 2084.69    49.3 2081.14    78.9 2080.62   177.6 2080.94   236.8 2081.88
   374.9 2081.94   384.8 2081.37   394.6 2079.59   434.1 2069.51   443.9  2068.1
   458.6 2064.73   463.7 2063.47   473.5 2062.98   473.6    2063   503.1 2067.96
     513 2070.26   522.9  2073.9   562.3 2091.68   572.2 2093.82   591.9 2102.51
   641.3 2119.87   680.7 2132.06   690.6 2133.38   759.6 2148.98   779.4 2155.02
   799.1 2159.97   818.8 2163.15   858.3 2172.92     878 2179.48   917.5 2189.12
#Mann= 3 , 0 , 0
       0      .1       0   458.6    .045       0   473.6      .1       0
Bank Sta=458.6,473.6
XS Rating Curve= 0 ,0
Exp/Cntr=0.3,0.1

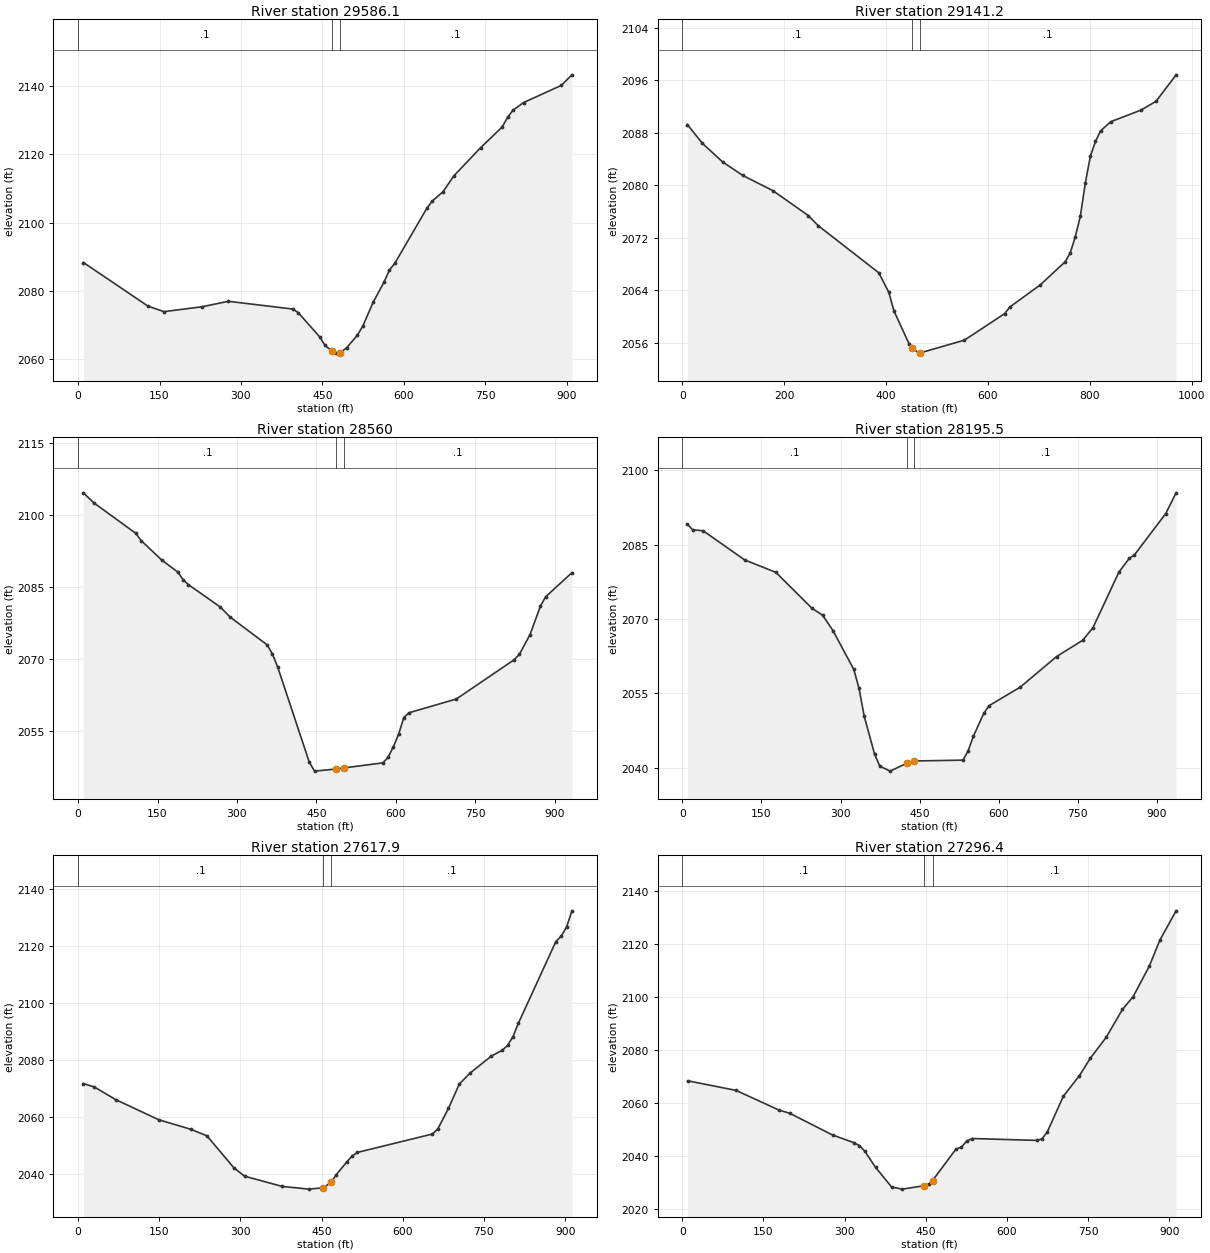
Type RM Length L Ch R = 1 ,29586.1 ,455.7,444.9,434.1
XS GIS Cut Line= 3
     2053594.106      306203.663     2053881.296      306556.575
     2054168.486      306909.487
#Sta/Elev= 30
     9.9 2088.31   128.6 2075.55   158.3 2073.92   227.5 2075.33     277 2076.95
   395.7 2074.68   405.5 2073.65   445.1 2066.55     455 2064.04   468.4 2062.27
   474.8 2061.77   483.4 2061.95   494.6 2063.31   514.3 2066.95   524.2 2069.58
     544 2076.76   563.8 2082.61   573.7 2086.13   583.6 2088.08   642.9 2104.28
   652.8 2106.34   672.6 2109.08   692.4 2113.71   741.8 2121.97   781.4 2128.01
   791.3 2130.81   801.2 2132.93     821 2135.19   890.2 2140.19     910  2143.3
#Mann= 3 , 0 , 0
       0      .1       0   468.4    .045       0   483.4      .1       0
Bank Sta=468.4,483.4
XS Rating Curve= 0 ,0
Exp/Cntr=0.3,0.1

Type RM Length L Ch R = 1 ,29141.2 ,604.1,581.2,557.9
XS GIS Cut Line= 2
     2053148.026      306691.718     2054037.837      307076.646
#Sta/Elev= 30
     9.9 2089.23    39.6 2086.36    79.1 2083.54   118.7 2081.48   178.1 2079.15
   247.3 2075.37   267.1 2073.81   385.8 2066.65   405.6 2063.65   415.5 2060.85
   445.2 2055.84   451.4 2055.14     465 2054.41   466.4 2054.43     554 2056.39
   633.1 2060.44     643 2061.43   702.4 2064.78   751.9 2068.34   761.8 2069.72
   771.6 2072.15   781.5 2075.26   791.4 2080.38   801.3 2084.45   811.2 2086.65
   821.1 2088.25   840.9 2089.65   900.3 2091.42   929.9 2092.75   969.5  2096.8
#Mann= 3 , 0 , 0
       0      .1       0   451.4    .045       0   466.4      .1       0
Bank Sta=451.4,466.4
XS Rating Curve= 0 ,0
Exp/Cntr=0.3,0.1

Type RM Length L Ch R = 1 ,28560   ,371.2,364.5,357.8
XS GIS Cut Line= 2
     2053197.711      307625.739     2054000.838      307151.578
#Sta/Elev= 30
     9.9 2104.62    29.8 2102.53   109.1 2096.17   119.1 2094.67   158.7 2090.55
   188.5 2088.11   198.4 2086.51   208.4  2085.5   267.9 2080.89   287.7  2078.7
   357.2 2072.95   367.1 2071.03     377 2068.32   436.6 2048.54   446.5 2046.67
   487.9 2047.11   502.9 2047.35   575.5 2048.39   585.4 2049.53   595.3 2051.71
   605.2 2054.32   615.2 2057.83   625.1 2058.83   714.4 2061.69   823.5 2069.86
   833.4    2071   853.3 2075.04   873.1 2081.01     883 2082.98   932.7    2088
#Mann= 3 , 0 , 0
       0      .1       0   487.9    .045       0   502.9      .1       0
Bank Sta=487.9,502.9
XS Rating Curve= 0 ,0
Exp/Cntr=0.3,0.1

Type RM Length L Ch R = 1 ,28195.5 ,539.8,577.7,571.6
XS GIS Cut Line= 2
     2053556.063      307978.179     2054189.054      307288.578
#Sta/Elev= 30
     9.9 2089.12    19.7 2088.01    39.4 2087.82   118.2 2081.94   177.4 2079.42
   246.3 2072.13     266 2070.79   285.7 2067.66   325.2 2059.82     335 2056.02
   344.9 2050.39   364.6 2042.71   374.4 2040.31   394.1 2039.31   425.1 2040.88
   440.1 2041.36   532.1 2041.53   541.9 2043.41   551.8 2046.36   571.5 2050.96
   581.3  2052.5   640.5 2056.25   709.4 2062.42   758.7 2065.69   778.4 2068.23
   827.7 2079.47   847.4 2082.26   857.2 2082.96   916.4 2091.28   936.1 2095.47
#Mann= 3 , 0 , 0
       0      .1       0   425.1    .045       0   440.1      .1       0
Bank Sta=425.1,440.1
XS Rating Curve= 0 ,0
Exp/Cntr=0.3,0.1

Type RM Length L Ch R = 1 ,27617.9 ,323.5,321.5,319.3
XS GIS Cut Line= 2
     2053963.391      308268.989     2054561.904      307580.074
#Sta/Elev= 30
     9.9 2071.63    29.8 2070.46    69.4 2066.03   148.8 2058.97   208.3  2055.6
   238.1 2053.31   287.7 2042.13   307.5 2039.18   376.9 2035.59   426.5 2034.63
   452.7  2035.1   467.7 2036.96   476.1 2039.45     496 2044.07   505.9 2046.16
   515.8 2047.48   654.7 2053.95   664.6 2055.71   684.4 2062.93   704.3 2071.43
   724.1 2075.29   763.8  2081.3   783.6 2083.28   793.6 2085.01   803.5 2088.04
   813.4  2092.7   882.8  2121.4   892.8 2123.36   902.7 2126.54   912.6  2132.2
#Mann= 3 , 0 , 0
       0      .1       0   452.7    .045       0   467.7      .1       0
Bank Sta=452.7,467.7
XS Rating Curve= 0 ,0
Exp/Cntr=0.3,0.1

Type RM Length L Ch R = 1 ,27296.4 ,258.7,257.1,255.4
XS GIS Cut Line= 2
     2054207.337      308535.229     2054723.997      307782.976
#Sta/Elev= 30
     9.9 2068.41    99.2 2064.79   178.6 2057.37   198.4 2056.17   277.7 2047.96
   317.4 2045.05   327.3 2043.95   337.3 2041.85   357.1 2035.79   386.9 2028.33
   406.7 2027.54   447.6 2028.84   456.3 2029.51   462.6 2030.79   505.9 2042.68
   515.8 2043.39   525.7 2045.65   535.7 2046.63   654.7 2045.92   664.6 2046.49
   674.5 2049.09   704.3 2062.61     734 2070.37   753.9 2076.86   783.6 2084.87
   813.4 2095.31   833.2 2100.15     863 2111.62   882.8 2121.55   912.6 2132.51
#Mann= 3 , 0 , 0
       0      .1       0   447.6    .045       0   462.6      .1       0
Bank Sta=447.6,462.6
XS Rating Curve= 0 ,0
Exp/Cntr=0.3,0.1

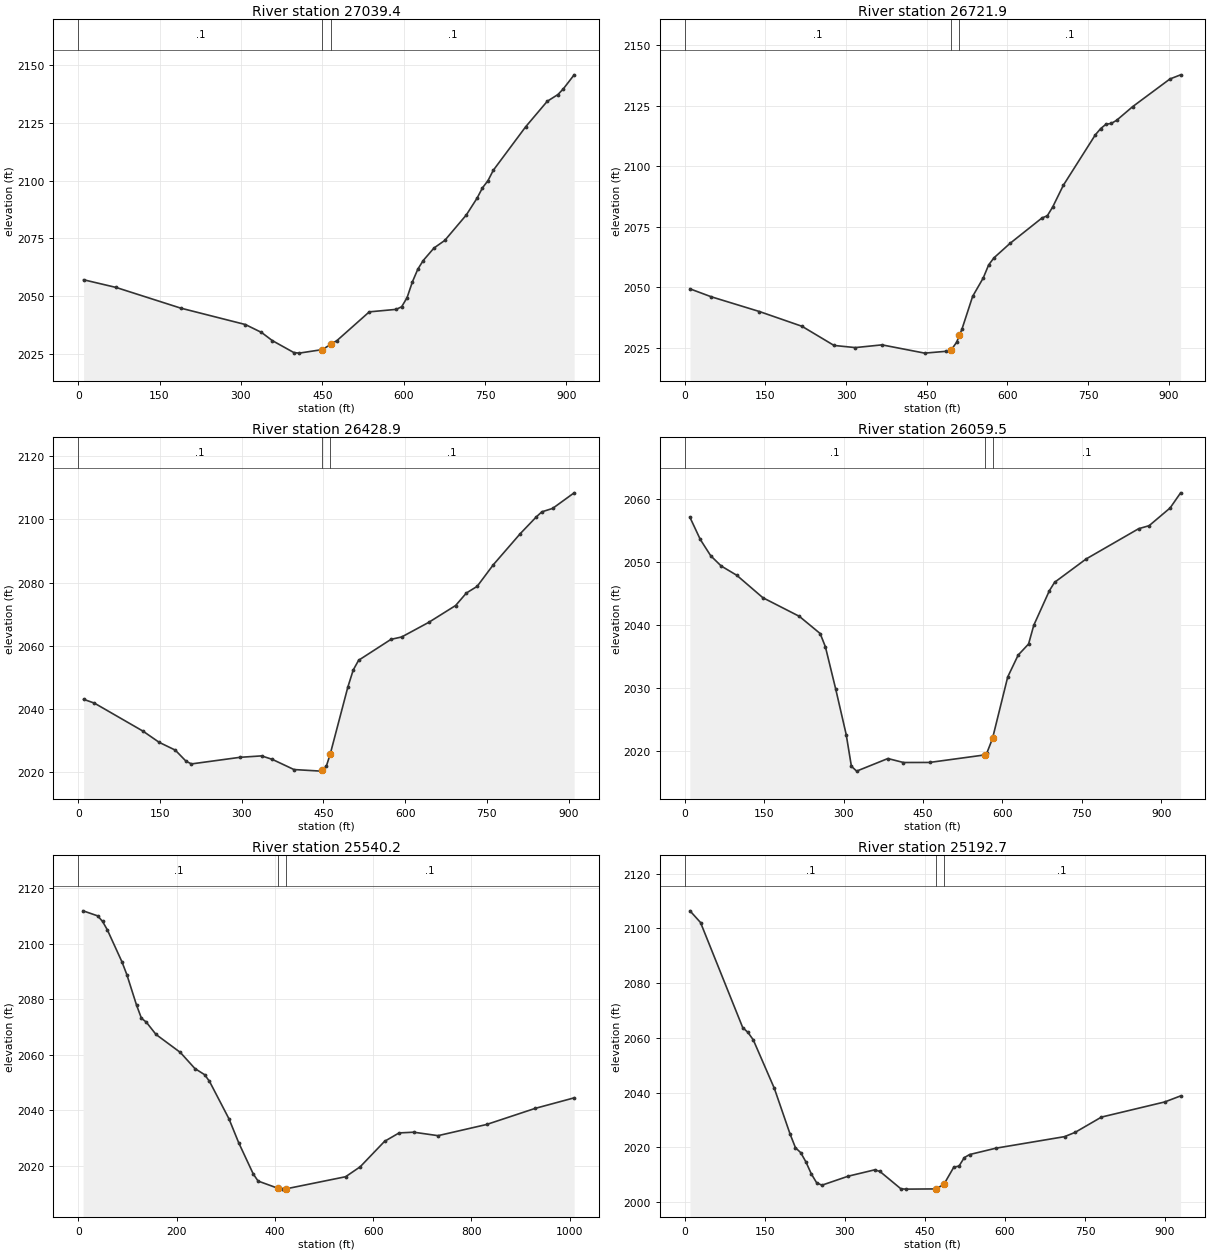
Type RM Length L Ch R = 1 ,27039.4 ,312.7,317.5,322.3
XS GIS Cut Line= 2
       2054450.7      308691.343     2054913.417      307902.827
#Sta/Elev= 30
     9.9 2057.08    69.6 2053.77   188.8 2044.82   308.1 2037.71   337.9 2034.29
   357.8 2030.76   397.5 2025.58   407.4 2025.33   450.3 2026.87   465.3 2029.11
     477 2030.76   536.6 2043.19   586.3 2044.27   596.3 2045.41   606.2 2049.29
   616.1 2056.18   626.1 2061.67     636  2065.4   655.9 2070.82   675.8 2074.11
   715.5 2085.13   735.4 2092.43   745.3 2096.87   755.3 2099.92   765.2 2104.45
   824.8 2123.25   864.6  2134.3   884.4 2137.24   894.4 2139.72   914.3 2145.77
#Mann= 3 , 0 , 0
       0      .1       0   450.3    .045       0   465.3      .1       0
Bank Sta=450.3,465.3
XS Rating Curve= 0 ,0
Exp/Cntr=0.3,0.1

Type RM Length L Ch R = 1 ,26721.9 ,289.7,293,295.4
XS GIS Cut Line= 2
     2054637.409      308765.054     2055262.167      308087.145
#Sta/Elev= 30
     9.9 2049.29    49.6    2046   138.8 2039.92   218.1  2033.8   277.6 2025.88
   317.2 2024.99   366.8 2026.12   446.1  2022.7   485.7 2023.45   495.8 2024.13
   505.6 2027.23   510.8  2030.1   515.5 2032.68   535.3 2046.19   555.1 2053.84
     565 2059.18   574.9 2062.12   604.7 2068.09   664.2 2078.62   674.1 2079.53
     684 2083.12   703.8 2092.11   763.3 2112.99   773.2 2115.58   783.1 2117.39
     793 2117.73   802.9 2119.02   832.7 2124.67   902.1 2136.13   921.9 2137.84
#Mann= 3 , 0 , 0
       0      .1       0   495.8    .045       0   510.8      .1       0
Bank Sta=495.8,510.8
XS Rating Curve= 0 ,0
Exp/Cntr=0.3,0.1

Type RM Length L Ch R = 1 ,26428.9 ,367.2,369.4,372.5
XS GIS Cut Line= 3
     2054814.241      308905.402     2055167.859      308618.474
     2055510.215       308318.88
#Sta/Elev= 30
     9.9 2043.11    29.7  2041.9   118.8 2033.05   148.5 2029.51   178.2 2027.03
     198 2023.51   207.9 2022.67     297 2024.76   336.6 2025.21   356.4  2024.1
     396 2020.89   445.5 2020.39   447.6 2020.72   455.4 2021.94   462.6  2025.8
   494.9 2046.97   504.8 2052.38   514.7 2055.46   574.1 2062.07   593.8 2062.83
   643.3 2067.44   692.7 2072.77   712.5 2076.73   732.3 2078.84     762 2085.69
   811.4 2095.51   841.1 2100.85     851 2102.41   870.8 2103.49   910.3 2108.42
#Mann= 3 , 0 , 0
       0      .1       0   447.6    .045       0   462.6      .1       0
Bank Sta=447.6,462.6
XS Rating Curve= 0 ,0
Exp/Cntr=0.3,0.1

Type RM Length L Ch R = 1 ,26059.5 ,526,519.3,512.7
XS GIS Cut Line= 3
     2054898.793      309229.351     2055485.274      308849.831
     2055599.652      308641.223
#Sta/Elev= 30
     9.8 2057.12    29.5 2053.58    49.2 2050.99    68.9 2049.37    98.4 2047.89
   147.6 2044.33   216.5 2041.37   255.8 2038.64   265.7 2036.54   285.3 2029.78
     305 2022.59   314.8 2017.56   324.7 2016.78   383.7 2018.78   413.2 2018.15
   462.4 2018.16   566.3 2019.35   570.7 2019.67   581.3 2021.97     610 2031.74
   629.7 2035.21   649.4 2036.98   659.2 2039.95   688.7 2045.45   698.6 2046.78
     758 2050.48   857.2 2055.29     877 2055.77   916.6 2058.58   936.5 2060.99
#Mann= 3 , 0 , 0
       0      .1       0   566.3    .045       0   581.3      .1       0
Bank Sta=566.3,581.3
XS Rating Curve= 0 ,0
Exp/Cntr=0.3,0.1

Type RM Length L Ch R = 1 ,25540.2 ,354.3,347.5,340.7
XS GIS Cut Line= 2
     2055149.441      309681.382     2055801.288      308911.081
#Sta/Elev= 30
     9.9 2111.87    39.6 2110.05    49.5 2108.06    59.4 2104.97      89 2093.48
    98.9  2088.9   118.7 2077.88   128.6 2073.16   138.5 2071.76   158.3 2067.31
   207.8 2060.83   237.4 2055.03   257.2 2052.81   267.1 2050.41   306.7 2036.92
   326.5  2028.3   356.2 2017.01     366 2014.47   407.2 2011.82   415.5 2011.56
   422.2 2011.64   544.1 2016.03   573.8 2019.62   623.3 2028.78   652.9 2031.82
   682.6 2032.08   732.1 2030.83     831 2034.86   929.9 2040.67  1009.1 2044.46
#Mann= 3 , 0 , 0
       0      .1       0   407.2    .045       0   422.2      .1       0
Bank Sta=407.2,422.2
XS Rating Curve= 0 ,0
Exp/Cntr=0.3,0.1

Type RM Length L Ch R = 1 ,25192.7 ,320.8,313.2,307.5
XS GIS Cut Line= 2
     2055562.916      309855.651      2055932.53      309003.252
#Sta/Elev= 30
     9.9  2106.4    29.7 2102.13   108.7 2063.76   118.6 2061.97   128.5 2059.26
     168 2041.53   197.7 2024.72   207.6 2019.84   217.4 2018.06   227.3 2014.61
   237.2 2010.31   247.1 2007.09     257 2006.16   306.4 2009.46   355.8 2011.77
   365.7  2011.2   405.2 2004.82   415.1 2004.73   470.5 2004.81   485.5 2006.44
   504.1 2012.73     514 2013.17   523.8 2016.23   533.7 2017.36   583.1 2019.69
   711.6  2023.9   731.4 2025.46   780.8 2031.05   899.4 2036.58   929.1 2038.79
#Mann= 3 , 0 , 0
       0      .1       0   470.5    .045       0   485.5      .1       0
Bank Sta=470.5,485.5
XS Rating Curve= 0 ,0
Exp/Cntr=0.3,0.1

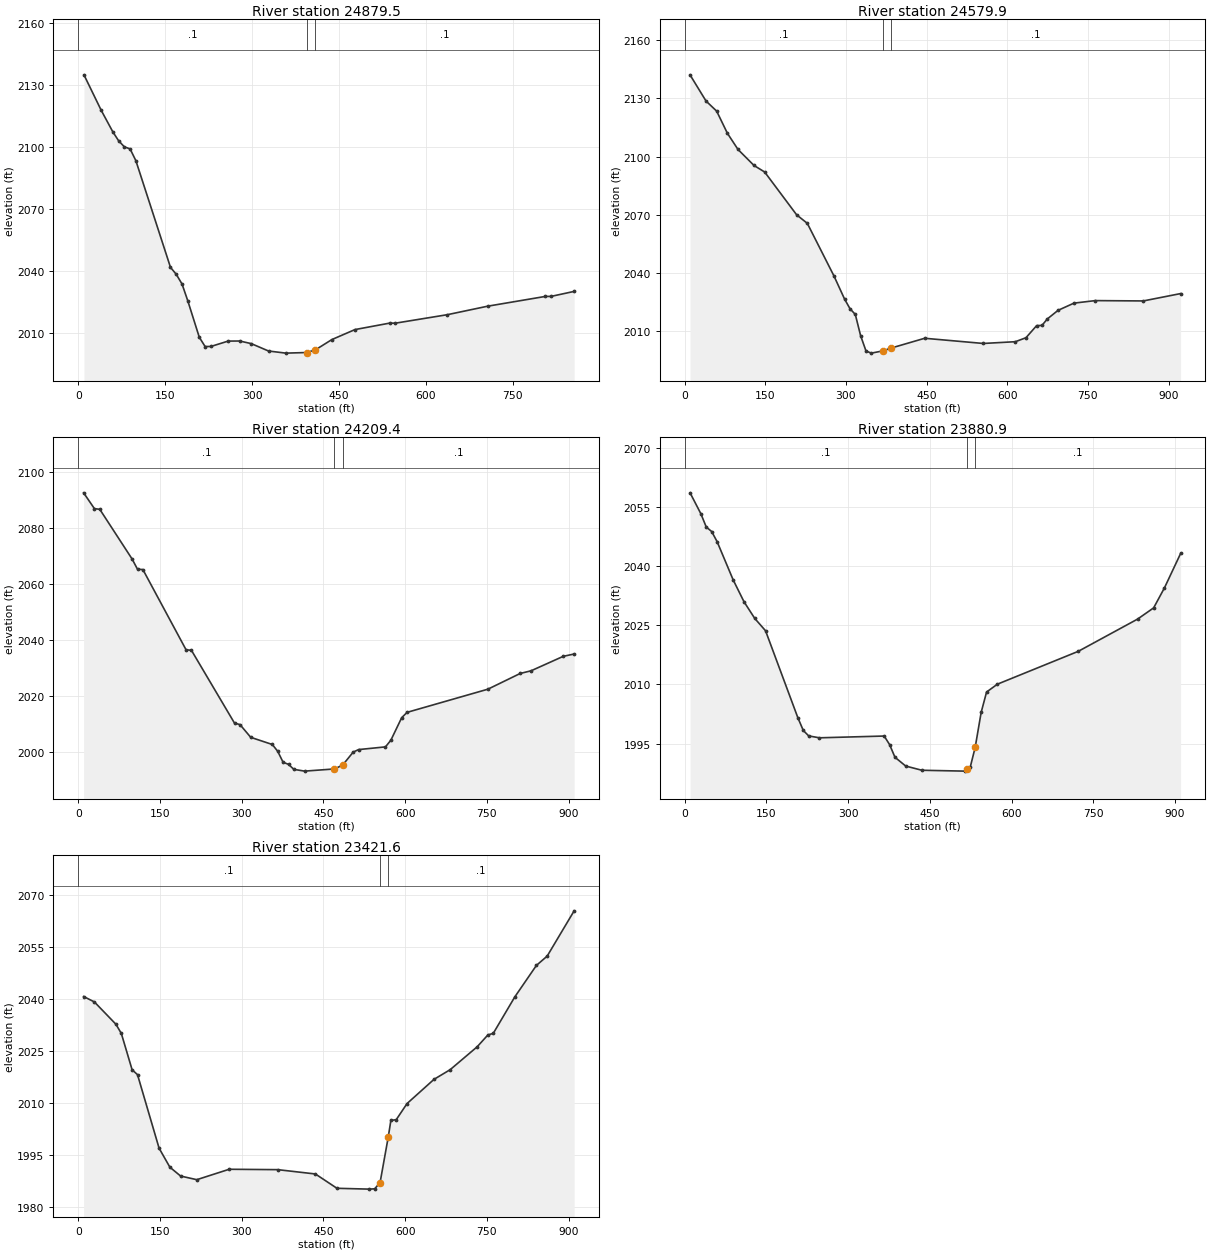
Type RM Length L Ch R = 1 ,24879.5 ,299.6,299.5,297.7
XS GIS Cut Line= 2
     2055886.215       309989.13     2056124.566      309167.422
#Sta/Elev= 30
     9.9 2135.04    39.8 2117.78    59.7 2107.43    69.6 2103.14    79.6 2100.16
    89.5 2099.16    99.5 2093.43   159.2 2041.78   169.1 2038.43   179.1 2033.72
     189 2025.62   208.9 2007.92   218.9 2003.44   228.8 2003.46   258.7 2006.07
   278.6 2006.11   298.5 2004.85   328.3 2001.27   358.1 2000.24   394.2 2000.53
   409.2 2001.82   437.7 2006.82   477.5 2011.65   537.2 2014.77   547.2 2014.75
   636.7 2018.85   706.3 2022.97   805.8  2027.7   815.8 2027.72   855.6 2030.14
#Mann= 3 , 0 , 0
       0      .1       0   394.2    .045       0   409.2      .1       0
Bank Sta=394.2,409.2
XS Rating Curve= 0 ,0
Exp/Cntr=0.3,0.1

Type RM Length L Ch R = 1 ,24579.9 ,371.2,370.6,369.9
XS GIS Cut Line= 2
     2056191.449      310126.313     2056270.329      309207.183
#Sta/Elev= 30
     9.9 2142.09    39.7  2128.6    59.5 2123.39    79.4 2112.01    99.2 2103.65
     129  2095.4   148.8 2092.03   208.3 2069.97   228.1  2065.6   277.7 2038.49
   297.6 2026.48   307.5 2021.64   317.4 2018.66   327.3  2007.7   337.3 1999.84
   347.2 1998.75   368.8  1999.9   383.8 2001.34   446.4  2006.4   555.5 2003.73
     615 2004.63   634.8 2006.68   654.7 2012.92   664.6 2013.02   674.5 2016.34
   694.4 2020.77   724.1  2024.5   763.8  2025.8   853.1 2025.63   922.5 2029.42
#Mann= 3 , 0 , 0
       0      .1       0   368.8    .045       0   383.8      .1       0
Bank Sta=368.8,383.8
XS Rating Curve= 0 ,0
Exp/Cntr=0.3,0.1

Type RM Length L Ch R = 1 ,24209.4 ,326.2,328.5,330.7
XS GIS Cut Line= 3
     2056544.448      310100.427     2056563.123      309645.699
     2056590.926      309191.569
#Sta/Elev= 30
     9.9 2092.57    29.7 2086.93    39.6 2086.67    98.9 2068.91   108.8 2065.26
   118.7 2065.14   197.9 2036.47   207.8 2036.27   286.9 2010.22   296.8 2009.74
   316.6 2005.17   356.2 2002.61   366.1 2000.18     376 1996.25   385.9 1995.52
   395.7 1993.72   415.5 1993.09   470.2 1993.87   485.2 1995.23   504.6 1999.89
   514.5 2000.79   563.9 2001.76   573.8 2004.16   593.6 2012.19   603.5  2014.1
   751.8 2022.38   811.2 2028.01     831 2028.95   890.3 2034.14   910.1 2034.95
#Mann= 3 , 0 , 0
       0      .1       0   470.2    .045       0   485.2      .1       0
Bank Sta=470.2,485.2
XS Rating Curve= 0 ,0
Exp/Cntr=0.3,0.1

Type RM Length L Ch R = 1 ,23880.9 ,455.5,459.3,463.1
XS GIS Cut Line= 3
     2056815.161      310113.308     2056879.069      309662.705
     2056952.001      309213.608
#Sta/Elev= 30
     9.9 2058.65    29.7 2053.34    39.6 2049.97    49.5 2048.83    59.4 2046.29
      89 2036.54   108.8 2031.01   128.6 2026.76   148.4 2023.63   207.8 2001.51
   217.7 1998.31   227.6 1996.93   247.3 1996.45   366.1  1996.9     376 1994.74
   385.9 1991.51   405.6 1989.28   435.3 1988.21   514.5 1987.99   518.1 1988.41
   524.3 1989.14   533.1 1994.02   544.1 2002.92     554 2008.07   573.8 2010.06
   722.2  2018.4     831 2026.58   860.6 2029.44   880.4 2034.51   910.1 2043.25
#Mann= 3 , 0 , 0
       0      .1       0   518.1    .045       0   533.1      .1       0
Bank Sta=518.1,533.1
XS Rating Curve= 0 ,0
Exp/Cntr=0.3,0.1

Type RM Length L Ch R = 1 ,23421.6 ,307.3,306.8,306.4
XS GIS Cut Line= 3
     2057167.289      310156.774      2057312.82      309725.665
     2057459.883      309295.095
#Sta/Elev= 30
     9.9 2040.77    29.7  2039.2    69.2 2032.75    79.1  2030.1    98.9 2019.59
   108.8 2018.18   148.4 1996.92   168.2 1991.43   187.9 1988.87   217.6 1987.82
     277 1990.83     366 1990.72   435.2 1989.47   474.8 1985.33   534.1 1985.09
     544 1985.18   553.9 1986.99   568.9 2000.16   573.7 2004.93   583.6 2005.18
   603.4 2009.83   652.8 2016.82   682.5 2019.62     732 2026.23   751.7 2029.66
   761.6 2030.12   801.2 2040.68   840.8 2049.77   860.5 2052.45     910 2065.54
#Mann= 3 , 0 , 0
       0      .1       0   553.9    .045       0   568.9      .1       0
Bank Sta=553.9,568.9
XS Rating Curve= 0 ,0
Exp/Cntr=0.3,0.1