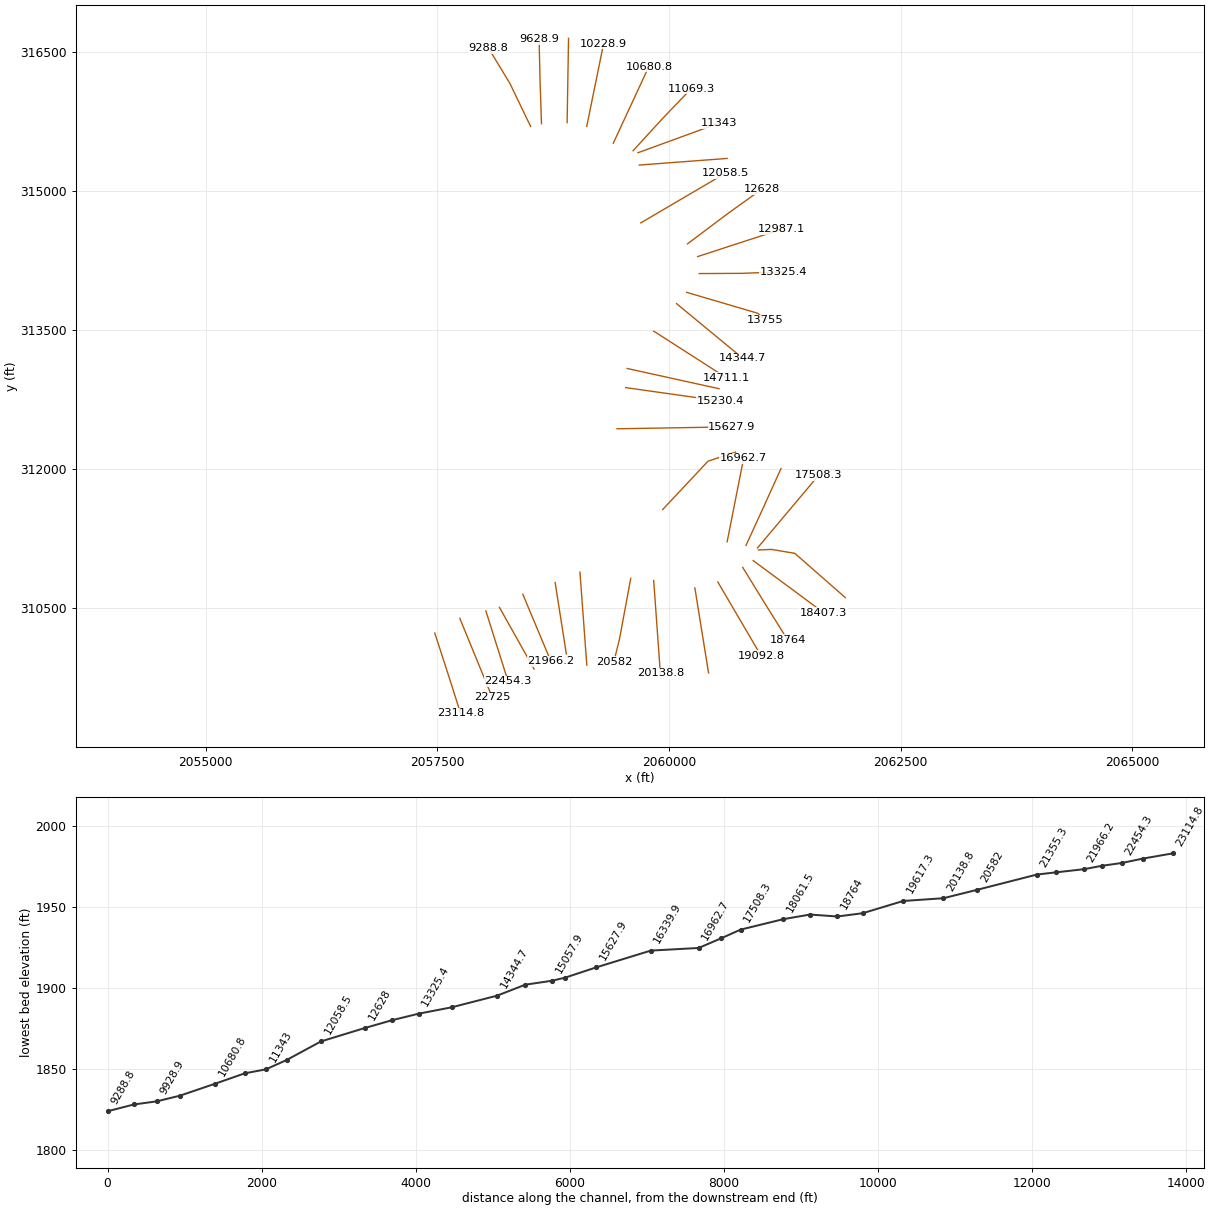
HEC-RAS study ABRMCRK.prj: ABRMCRK

--- ABRMCRK.g01 (geometry) --- (continued)

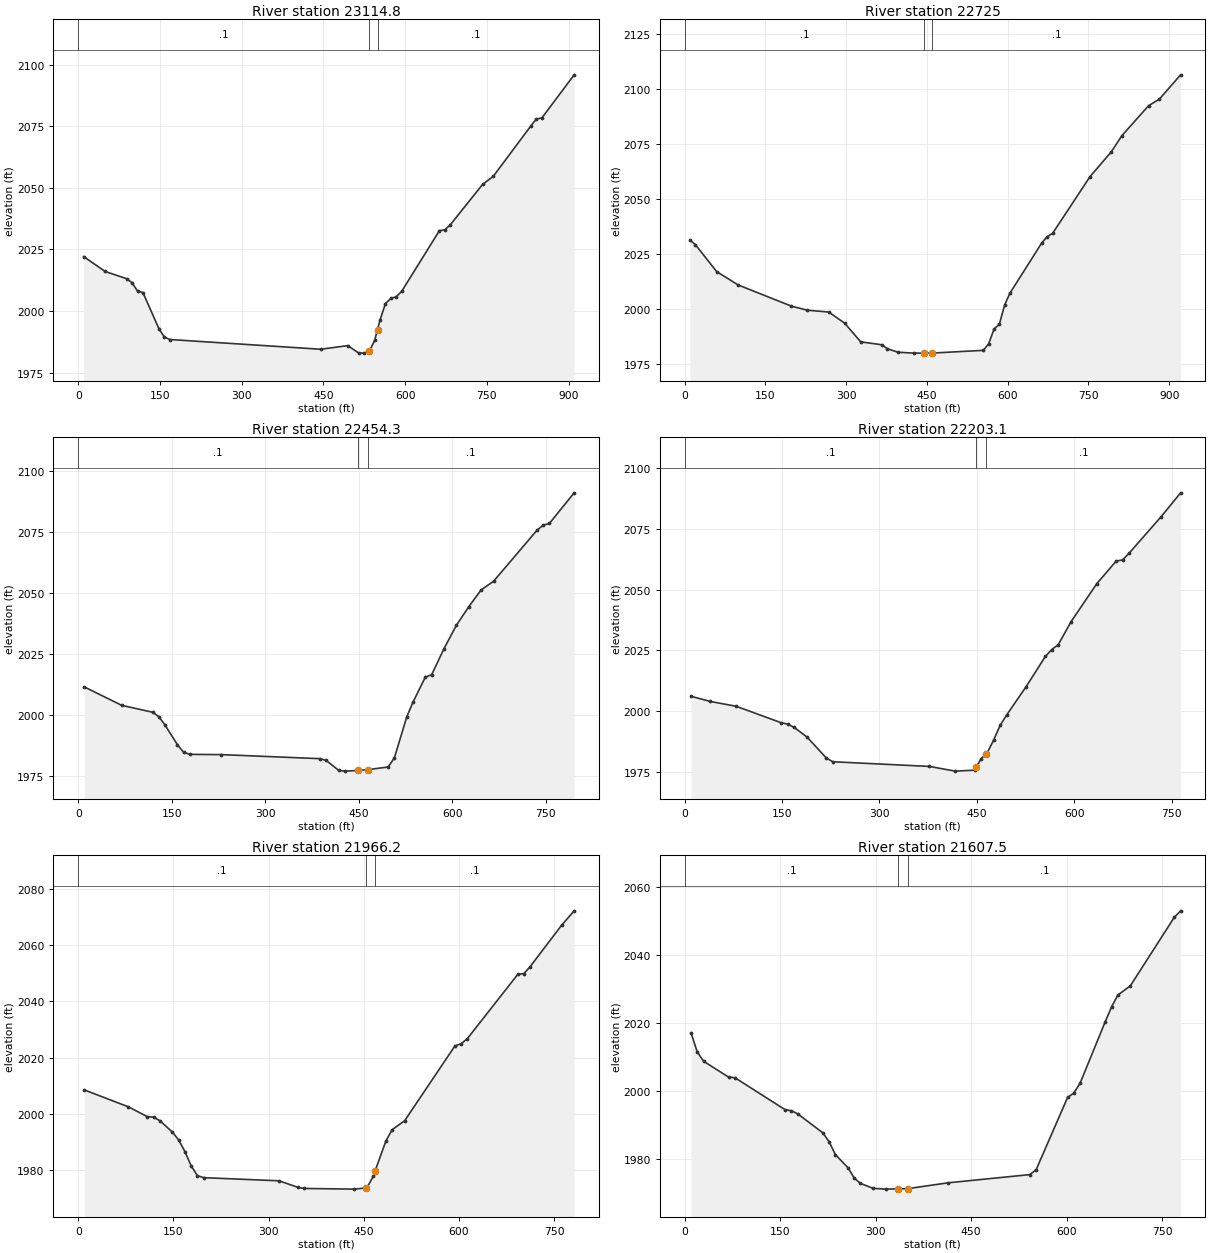
Type RM Length L Ch R = 1 ,23114.8 ,389.2,389.8,390.3
XS GIS Cut Line= 3
     2057471.425      310233.903     2057611.897      309801.123
     2057750.246      309367.668
#Sta/Elev= 30
     9.9 2022.13    49.5 2016.08      89 2013.15    98.9 2011.52   108.8 2008.12
   118.7 2007.56   148.4 1992.73   158.3 1989.49   168.2  1988.5   445.1 1984.55
   494.6 1986.03   514.4 1983.07   524.2 1982.98   534.2 1983.69     544 1988.19
   549.2 1992.54   553.9 1996.47   563.8  2003.1   573.7 2005.17   583.6 2005.85
   593.5 2008.02   662.7 2032.62   672.6 2032.98   682.5 2034.95   741.9 2051.37
   761.6 2054.67   830.9  2075.2   840.8 2077.94   850.7 2078.32     910 2095.82
#Mann= 3 , 0 , 0
       0      .1       0   534.2    .045       0   549.2      .1       0
Bank Sta=534.2,549.2
XS Rating Curve= 0 ,0
Exp/Cntr=0.3,0.1

Type RM Length L Ch R = 1 ,22725   ,271.6,270.7,269.8
XS GIS Cut Line= 2
     2057741.442      310392.932     2058091.279      309540.831
#Sta/Elev= 30
     9.9 2031.21    19.8 2029.18    59.4 2016.87      99 2010.81   198.1 2001.15
   227.8 1999.28   267.4 1998.45   297.1  1993.4   326.8 1984.89   366.5 1983.53
   376.4 1981.74   396.2 1980.15   425.9 1979.74   444.4 1979.75   459.4 1979.76
   554.7 1981.01   564.6    1984   574.5 1990.67   584.4 1992.87   594.3  2001.7
   604.2 2007.08   663.6 2030.08   673.5 2032.81   683.4 2034.29   752.7 2060.08
   792.4 2071.42   812.2 2078.82   861.7 2092.45   881.5 2095.36   921.1 2106.47
#Mann= 3 , 0 , 0
       0      .1       0   444.4    .045       0   459.4      .1       0
Bank Sta=444.4,459.4
XS Rating Curve= 0 ,0
Exp/Cntr=0.3,0.1

Type RM Length L Ch R = 1 ,22454.3 ,246.7,251.2,255.8
XS GIS Cut Line= 2
      2058022.73       310472.15     2058262.425      309713.684
#Sta/Elev= 30
     9.9 2011.51    69.6 2004.01   119.3 2001.16   129.3 1999.36   139.2 1995.95
   159.1 1987.86     169  1984.8     179 1983.91   228.7 1983.82   387.8 1982.15
   397.7 1981.44   417.6 1977.39   427.5 1977.05   449.1 1977.33   464.1 1977.65
   497.1 1978.74   507.1 1982.49     527 1999.33   536.9 2005.27   556.8  2015.6
   566.8 2016.48   586.6 2027.16   606.5 2036.75   626.4 2044.39   646.3 2051.28
   666.2  2054.8   735.8 2075.69   745.7 2077.75   755.7 2078.47   795.4 2091.01
#Mann= 3 , 0 , 0
       0      .1       0   449.1    .045       0   464.1      .1       0
Bank Sta=449.1,464.1
XS Rating Curve= 0 ,0
Exp/Cntr=0.3,0.1

Type RM Length L Ch R = 1 ,22203.1 ,239.5,236.9,234.3
XS GIS Cut Line= 2
      2058169.14      310511.206      2058543.05      309845.352
#Sta/Elev= 30
     9.9 2006.14    39.7 2004.02    79.3 2002.05   148.8 1995.27   158.7 1994.72
   168.6 1993.37   188.4  1989.4   218.2 1980.75   228.1 1979.24   376.9 1977.31
   416.5 1975.38   446.3 1975.77   448.9 1976.98   456.2 1980.38   463.9 1982.42
   466.1 1983.01     476 1988.29     486 1994.29   495.9  1998.5   525.6 2010.04
   555.4 2022.53   565.3 2025.39   575.2 2027.35   595.1 2036.88   634.7 2052.51
   664.5 2061.77   674.4 2062.25   684.3 2064.97   733.9 2080.09   763.7 2089.83
#Mann= 3 , 0 , 0
       0      .1       0   448.9    .045       0   463.9      .1       0
Bank Sta=448.9,463.9
XS Rating Curve= 0 ,0
Exp/Cntr=0.3,0.1

Type RM Length L Ch R = 1 ,21966.2 ,360.7,358.7,354.5
XS GIS Cut Line= 2
     2058422.041      310651.435     2058724.069      309930.285
#Sta/Elev= 30
     9.9 2008.51    79.2 2002.51   108.9 1999.02   118.8 1998.84   128.7 1997.61
   148.5 1993.53   158.3 1990.74   168.2 1986.62   178.1 1981.51     188 1978.01
   197.9 1977.32   316.7  1976.2   346.4 1973.87   356.3 1973.48   435.5 1973.24
     453 1973.66   455.3 1973.78   465.1 1977.81     468 1979.71   484.9 1990.29
   494.8 1994.38   514.6 1997.58   593.8 2024.17   603.7 2024.98   613.6 2026.83
   692.8 2049.62   702.7 2049.95   712.6 2052.45     762 2067.13   781.8 2072.26
#Mann= 3 , 0 , 0
       0      .1       0     453    .045       0     468      .1       0
Bank Sta=453,468
XS Rating Curve= 0 ,0
Exp/Cntr=0.3,0.1

Type RM Length L Ch R = 1 ,21607.5 ,255.5,252.2,248.8
XS GIS Cut Line= 2
     2058770.604      310778.126     2058891.419      310008.805
#Sta/Elev= 30
     9.9 2017.16    19.7 2011.54    29.6 2008.82      69 2004.14    78.9 2003.97
   157.7  1994.6   167.6 1994.29   177.4 1993.39   216.9 1987.83   226.7 1985.24
   236.6 1981.44   256.3 1977.62   266.2 1974.57     276 1972.99   295.7 1971.55
   315.4 1971.31   335.6 1971.39   350.6 1971.46     414 1973.17   542.2 1975.57
     552 1977.03   601.3 1998.19   611.2  1999.5     621 2002.39   660.5 2020.43
   670.3  2024.7   680.2  2028.2   699.9 2030.92   768.9 2051.01   778.8  2052.9
#Mann= 3 , 0 , 0
       0      .1       0   335.6    .045       0   350.6      .1       0
Bank Sta=335.6,350.6
XS Rating Curve= 0 ,0
Exp/Cntr=0.3,0.1

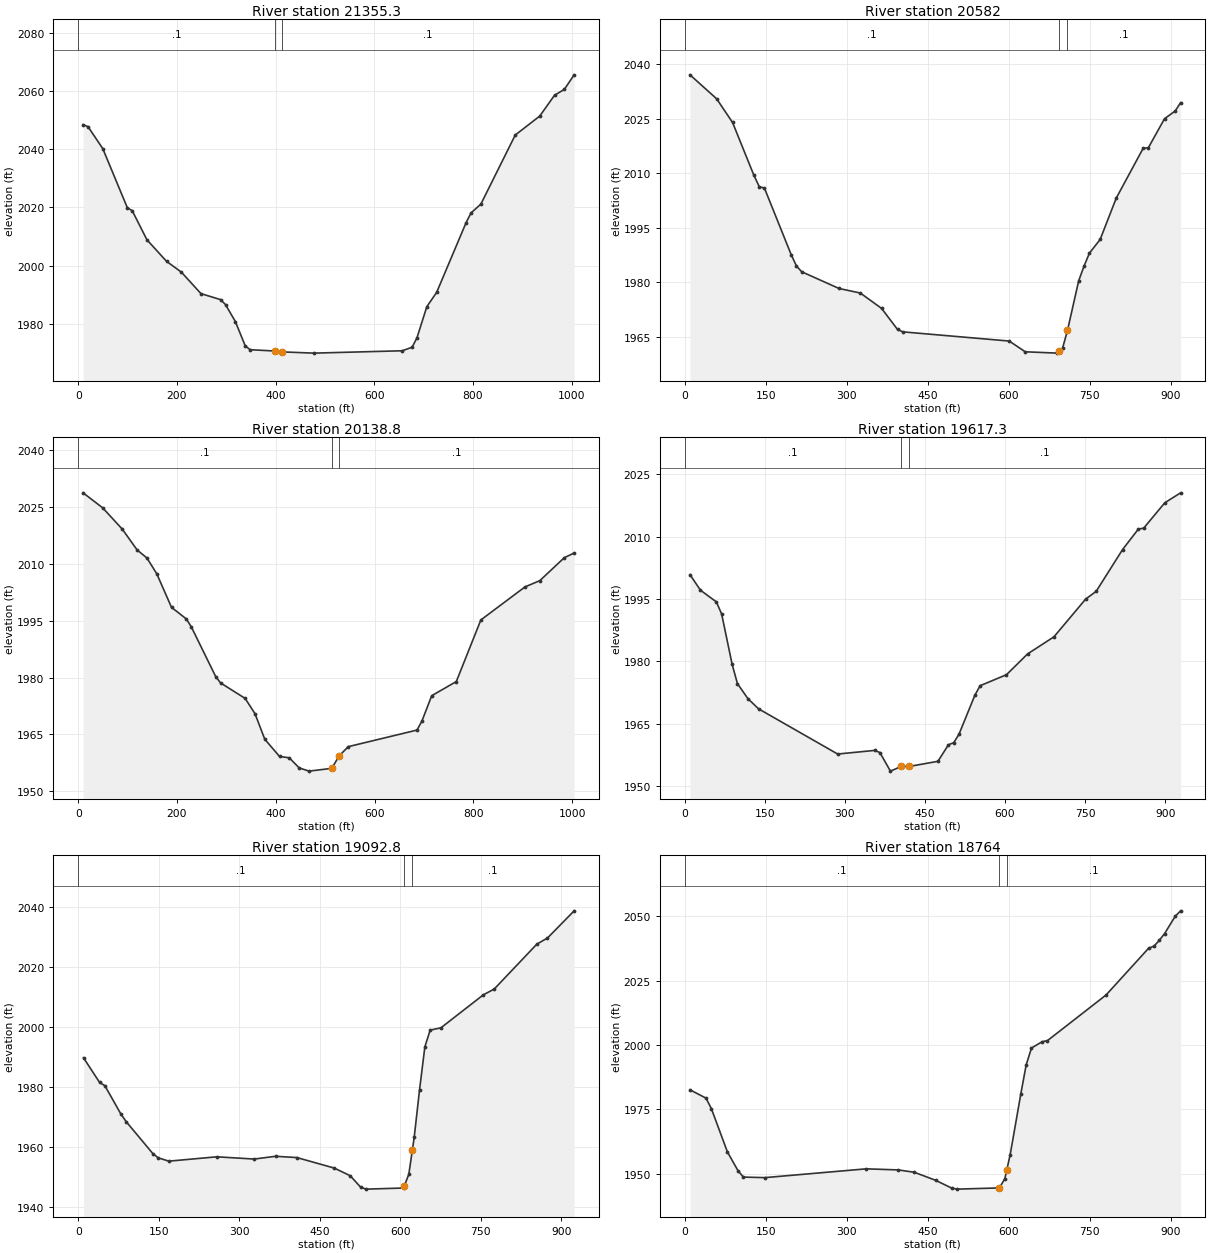
Type RM Length L Ch R = 1 ,21355.3 ,780.7,773.3,766.3
XS GIS Cut Line= 2
     2059038.447      310890.465     2059112.401      309887.988
#Sta/Elev= 30
      10 2048.38    19.9 2047.69    49.8 2040.15    99.5 2019.89   109.5 2018.83
   139.3 2008.85   179.1 2001.45     209 1997.76   248.8 1990.37   288.6 1988.31
   298.6 1986.59   318.5 1980.79   338.4 1972.49   348.3 1971.12   398.7 1970.66
   413.7 1970.36   477.7 1969.94   656.9 1970.75   676.8 1971.97   686.7 1975.24
   706.6 1985.89   726.5  1990.8   786.2 2014.74   796.2 2018.09   816.1 2021.09
   885.8 2044.81   935.5 2051.34   965.4 2058.47   985.3 2060.49  1005.2 2065.49
#Mann= 3 , 0 , 0
       0      .1       0   398.7    .045       0   413.7      .1       0
Bank Sta=398.7,413.7
XS Rating Curve= 0 ,0
Exp/Cntr=0.3,0.1

Type RM Length L Ch R = 1 ,20582   ,437.4,443.1,448.6
XS GIS Cut Line= 3
     2059586.748      310823.241     2059464.277      310164.903
     2059404.263      309924.145
#Sta/Elev= 30
     9.8 2037.08    59.1  2030.5    88.6 2023.98     128 2009.49   137.9 2006.36
   147.7 2005.89     197 1987.67   206.8 1984.52   216.6 1982.92   285.6 1978.33
     325 1977.08   364.4 1972.85   393.9 1967.06   403.7  1966.4   600.7 1963.87
   630.2 1960.92   689.5 1960.55   693.4  1961.1   699.4 1961.94   708.4 1966.78
   729.2 1980.46   739.1 1984.48     749 1988.04   768.9 1991.81   798.7 2003.19
   848.3 2016.83   858.2 2017.06     888 2025.01   907.8 2027.14   917.8 2029.43
#Mann= 3 , 0 , 0
       0      .1       0   693.4    .045       0   708.4      .1       0
Bank Sta=693.4,708.4
XS Rating Curve= 0 ,0
Exp/Cntr=0.3,0.1

Type RM Length L Ch R = 1 ,20138.8 ,513.5,521.6,534.7
XS GIS Cut Line= 2
     2059834.425      310800.141     2059906.436      309798.562
#Sta/Elev= 30
     9.9 2028.77    49.7 2024.79    89.5 2019.14   119.3 2013.69   139.2 2011.56
   159.1 2007.39   188.9 1998.54   218.7  1995.5   228.7 1993.46   278.4 1980.26
   288.3 1978.58     338  1974.5   357.9 1970.48   377.8 1963.71   407.6 1959.18
   427.5 1958.81   447.4 1956.15   467.3  1955.3   513.4 1956.03   528.4 1959.33
   546.8 1961.76     686 1966.14     696 1968.53   715.8 1975.21   765.6 1978.95
   815.3 1995.21   904.7 2003.94   934.6 2005.58   984.3 2011.65  1004.2 2012.88
#Mann= 3 , 0 , 0
       0      .1       0   513.4    .045       0   528.4      .1       0
Bank Sta=513.4,528.4
XS Rating Curve= 0 ,0
Exp/Cntr=0.3,0.1

Type RM Length L Ch R = 1 ,19617.3 ,519.5,524.5,521.1
XS GIS Cut Line= 2
     2060278.702      310720.786     2060426.552      309803.859
#Sta/Elev= 30
     9.9 2000.85    29.6  1997.1    59.3  1994.3    69.2  1991.4    88.9 1979.27
    98.8 1974.64   118.6    1971   138.3 1968.59   286.5 1957.71   355.7 1958.58
   365.6 1958.07   385.3  1953.6     406 1954.74     421 1954.74   474.3 1955.96
     494 1959.94   503.9 1960.44   513.8 1962.49   543.4 1971.83   553.3 1974.14
   602.7 1976.79   642.2 1981.78   691.6  1985.9   750.9 1994.96   770.7 1996.84
   820.1 2006.88   849.7 2011.81   859.6 2012.02   899.1 2018.12   928.8 2020.52
#Mann= 3 , 0 , 0
       0      .1       0     406    .045       0     421      .1       0
Bank Sta=406,421
XS Rating Curve= 0 ,0
Exp/Cntr=0.3,0.1

Type RM Length L Ch R = 1 ,19092.8 ,328.2,328.9,329.5
XS GIS Cut Line= 2
     2060526.816      310784.128     2060994.372      309987.247
#Sta/Elev= 30
     9.9 1989.85    39.7 1981.67    49.7 1980.54    79.5  1971.1    89.4 1968.55
   139.1 1957.89     149 1956.49   168.9 1955.38   258.3 1956.83   327.8 1956.08
   367.6    1957   407.3 1956.58   476.9 1953.08   506.7 1950.52   526.5 1946.63
   536.5 1946.05     606 1946.42   607.4 1947.07   615.9    1951   622.4 1958.97
   625.9 1963.27   635.8 1979.05   645.8 1993.52   655.7 1999.08   675.6 1999.84
     755 2010.89   774.9 2012.76   854.4 2027.76   874.2  2029.8   923.9 2038.87
#Mann= 3 , 0 , 0
       0      .1       0   607.4    .045       0   622.4      .1       0
Bank Sta=607.4,622.4
XS Rating Curve= 0 ,0
Exp/Cntr=0.3,0.1

Type RM Length L Ch R = 1 ,18764   ,348.4,356.6,364.8
XS GIS Cut Line= 3
     2060795.703        310941.2     2061039.132      310545.558
     2061279.538      310161.238
#Sta/Elev= 30
     9.9 1982.58    39.5 1979.35    49.4 1975.28    79.1 1958.47    98.8 1951.14
   108.7  1948.7   148.3 1948.48     336  1951.9   395.3 1951.48     425 1950.57
   464.5 1947.44   494.1 1944.43     504 1944.02   581.1 1944.48   582.8 1944.56
   592.6 1948.11   596.1 1951.41   602.5 1957.46   622.2 1981.07   632.1  1992.3
   641.9 1998.82   661.6 2001.27   671.5  2001.7   779.9 2019.41   858.7 2037.58
   868.6 2038.37   878.4 2040.64   888.3 2043.28     908 2050.02   917.9  2052.1
#Mann= 3 , 0 , 0
       0      .1       0   581.1    .045       0   596.1      .1       0
Bank Sta=581.1,596.1
XS Rating Curve= 0 ,0
Exp/Cntr=0.3,0.1

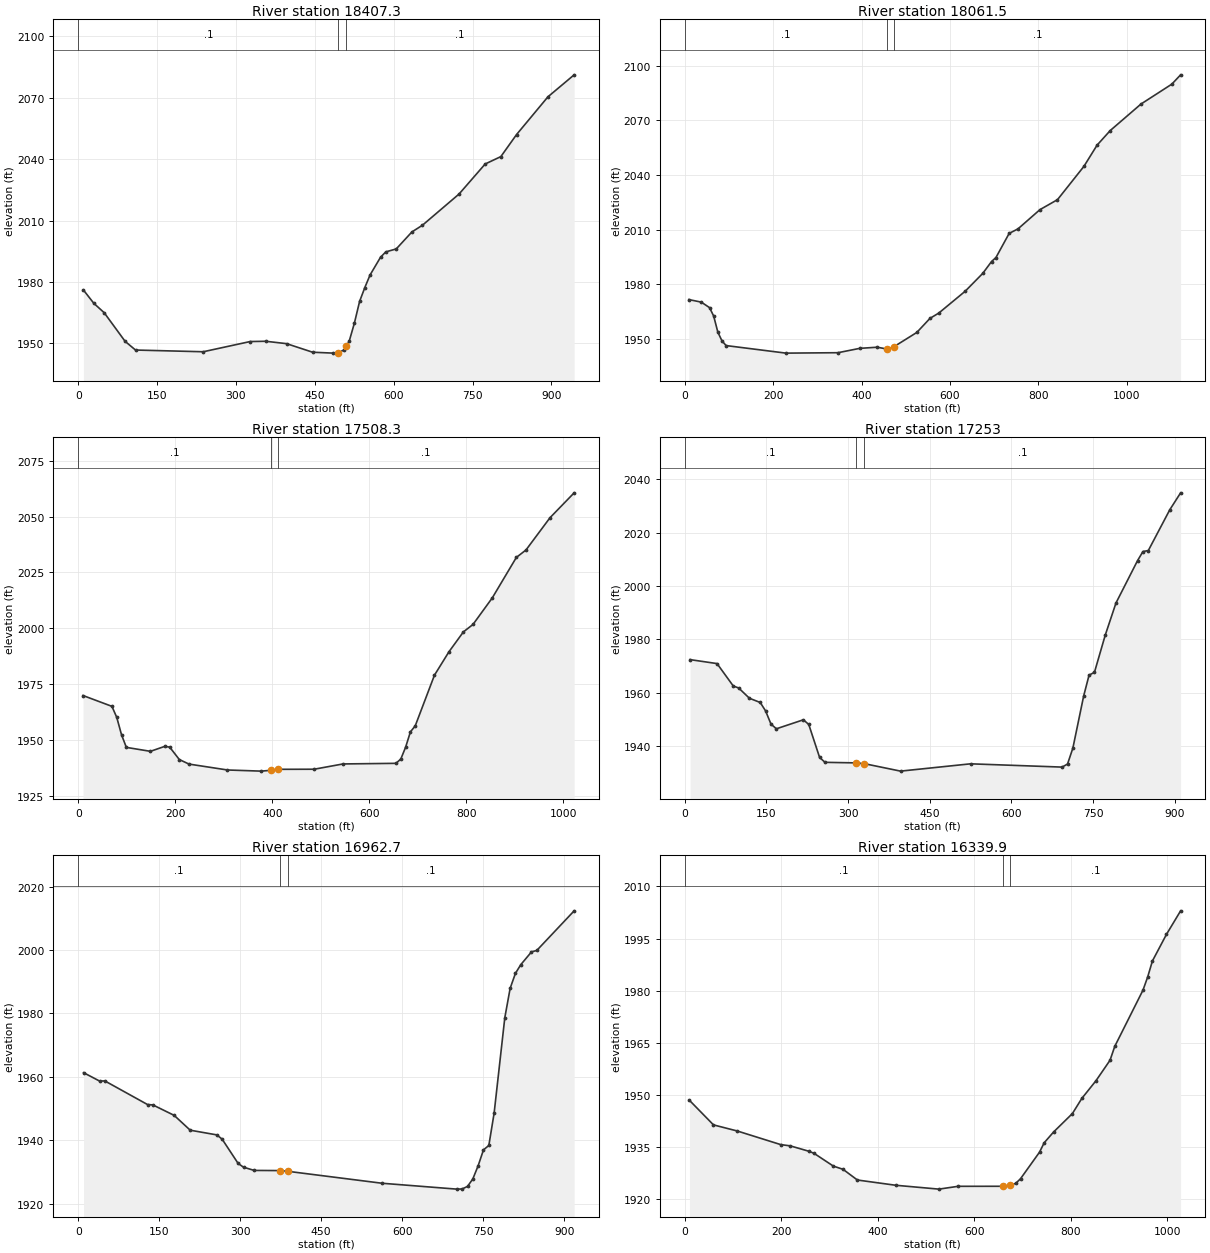
Type RM Length L Ch R = 1 ,18407.3 ,347.9,345.8,344
XS GIS Cut Line= 3
     2060908.425      311014.996     2061307.077      310720.878
      2061666.83      310454.111
#Sta/Elev= 30
     9.9 1976.08    29.7 1969.57    49.5 1964.95    89.2 1950.98     109 1946.73
   237.8 1945.89     327 1950.88   356.7 1951.02   396.3 1949.85   445.9 1945.66
   485.5 1945.22   494.7  1945.4   505.4 1946.79   509.7 1948.59   515.3 1950.93
   525.3 1959.88   535.2  1970.5   545.2  1977.3   555.1 1983.42     575 1992.08
     585 1994.71   604.9 1996.15   634.7 2004.46   654.7 2007.73   724.3 2022.97
   774.1 2037.68   803.9 2041.29   833.8 2052.08   893.5 2070.53   943.3 2081.26
#Mann= 3 , 0 , 0
       0      .1       0   494.7    .045       0   509.7      .1       0
Bank Sta=494.7,509.7
XS Rating Curve= 0 ,0
Exp/Cntr=0.3,0.1

Type RM Length L Ch R = 1 ,18061.5 ,520.6,553.2,585.9
XS GIS Cut Line= 4
     2060965.332       311129.79     2061105.801      311135.736
     2061357.319      311093.386     2061903.503      310615.475
#Sta/Elev= 30
     9.4 1971.72    37.5 1970.33    56.2 1967.31    65.6 1962.67      75 1953.85
    84.4 1949.05    93.7 1946.51   228.9 1942.37   346.6  1942.6   395.7 1944.98
   435.4 1945.61   458.3 1944.59   473.3 1945.91   524.9 1953.71   554.7 1961.43
   574.6 1964.33   634.3  1976.3     674 1986.08   693.9 1992.58   703.8 1994.75
   733.7    2008   753.6 2010.46   803.3 2021.01     843 2026.49   902.7 2044.72
   932.5 2056.37   962.3 2064.38  1031.9 2078.92  1101.5  2089.8  1121.4 2094.91
#Mann= 3 , 0 , 0
       0      .1       0   458.3    .045       0   473.3      .1       0
Bank Sta=458.3,473.3
XS Rating Curve= 0 ,0
Exp/Cntr=0.3,0.1

Type RM Length L Ch R = 1 ,17508.3 ,245.2,255.2,265.1
XS GIS Cut Line= 2
     2060955.151      311151.761     2061613.632      311933.708
#Sta/Elev= 30
     9.9  1969.8    69.5 1964.95    79.4 1960.03    89.3 1952.21    99.2 1946.57
   148.9  1944.8   178.6 1947.04   188.6 1946.67   208.4 1941.13   228.3 1939.09
   307.7 1936.44   377.1 1935.93     397 1936.28     412 1936.74   486.3 1936.78
   545.9 1939.15     655 1939.42     665 1941.36   674.9 1946.66   684.8 1953.53
   694.7  1956.2   734.4 1978.94   764.2 1989.39     794 1998.31   813.8 2001.65
   853.5 2013.53   903.2 2031.68     923    2035   972.6 2049.48  1022.3 2060.61
#Mann= 3 , 0 , 0
       0      .1       0     397    .045       0     412      .1       0
Bank Sta=397,412
XS Rating Curve= 0 ,0
Exp/Cntr=0.3,0.1

Type RM Length L Ch R = 1 ,17253   ,284.9,290.3,295.7
XS GIS Cut Line= 3
     2060830.832      311178.949     2061020.743      311593.179
      2061208.44      312007.434
#Sta/Elev= 30
     9.9 1972.34    59.4 1970.86    89.2 1962.46    99.1 1961.71   118.9 1957.85
   138.7 1956.27   148.6 1953.09   158.5 1948.15   168.4 1946.41   217.9 1949.78
   227.8 1948.03   247.7 1935.67   257.6 1933.83   314.3 1933.62   329.3 1933.35
   396.3 1930.53   524.9 1933.27     693 1932.04   702.9  1933.2   712.7 1939.17
   732.5  1958.7   742.4 1966.52   752.3 1967.58   772.1 1981.51   791.8 1993.57
   831.4 2009.46   841.3 2012.87   851.2 2013.25   890.7 2028.57   910.5 2034.89
#Mann= 3 , 0 , 0
       0      .1       0   314.3    .045       0   329.3      .1       0
Bank Sta=314.3,329.3
XS Rating Curve= 0 ,0
Exp/Cntr=0.3,0.1

Type RM Length L Ch R = 1 ,16962.7 ,631.2,622.8,610.8
XS GIS Cut Line= 2
     2060627.275      311218.567      2060805.55      312119.456
#Sta/Elev= 30
     9.9 1961.33    39.5 1958.69    49.4 1958.72   128.4 1951.27   138.2 1951.16
   177.7 1947.86   207.4 1943.18   256.7  1941.7   266.6 1940.34   296.2 1932.68
   306.1 1931.51   325.9 1930.49   373.2 1930.44   388.2 1930.21   562.9 1926.44
   701.1 1924.59     711 1924.64   720.9 1925.45   730.7 1927.78   740.6 1931.96
   750.5 1936.98   760.4 1938.36   770.2 1948.55     790 1978.69   799.9 1987.96
   809.7 1992.68   819.6 1995.41   839.4 1999.44   849.2 1999.89   918.4 2012.39
#Mann= 3 , 0 , 0
       0      .1       0   373.2    .045       0   388.2      .1       0
Bank Sta=373.2,388.2
XS Rating Curve= 0 ,0
Exp/Cntr=0.3,0.1

Type RM Length L Ch R = 1 ,16339.9 ,733.2,712,694.3
XS GIS Cut Line= 3
     2059931.473      311565.703     2060421.488      312087.721
     2060718.064      312184.678
#Sta/Elev= 30
     9.9 1948.48    59.7 1941.42   109.4 1939.65   198.9 1935.76   218.8 1935.39
   258.5  1933.8   268.5 1933.21   308.3 1929.56   328.2 1928.65     358 1925.57
   437.5 1924.06     527 1922.95   566.8 1923.76   659.3 1923.77   674.3 1924.09
   686.1  1924.6   696.1 1925.93   735.5 1933.57   745.2 1936.28   764.7 1939.38
   803.7 1944.68   823.2 1949.03   852.5 1954.11   881.7 1960.01   891.5    1964
     950 1980.17   959.7 1983.94   969.5 1988.54   998.7 1996.21    1028 2002.97
#Mann= 3 , 0 , 0
       0      .1       0   659.3    .045       0   674.3      .1       0
Bank Sta=659.3,674.3
XS Rating Curve= 0 ,0
Exp/Cntr=0.3,0.1

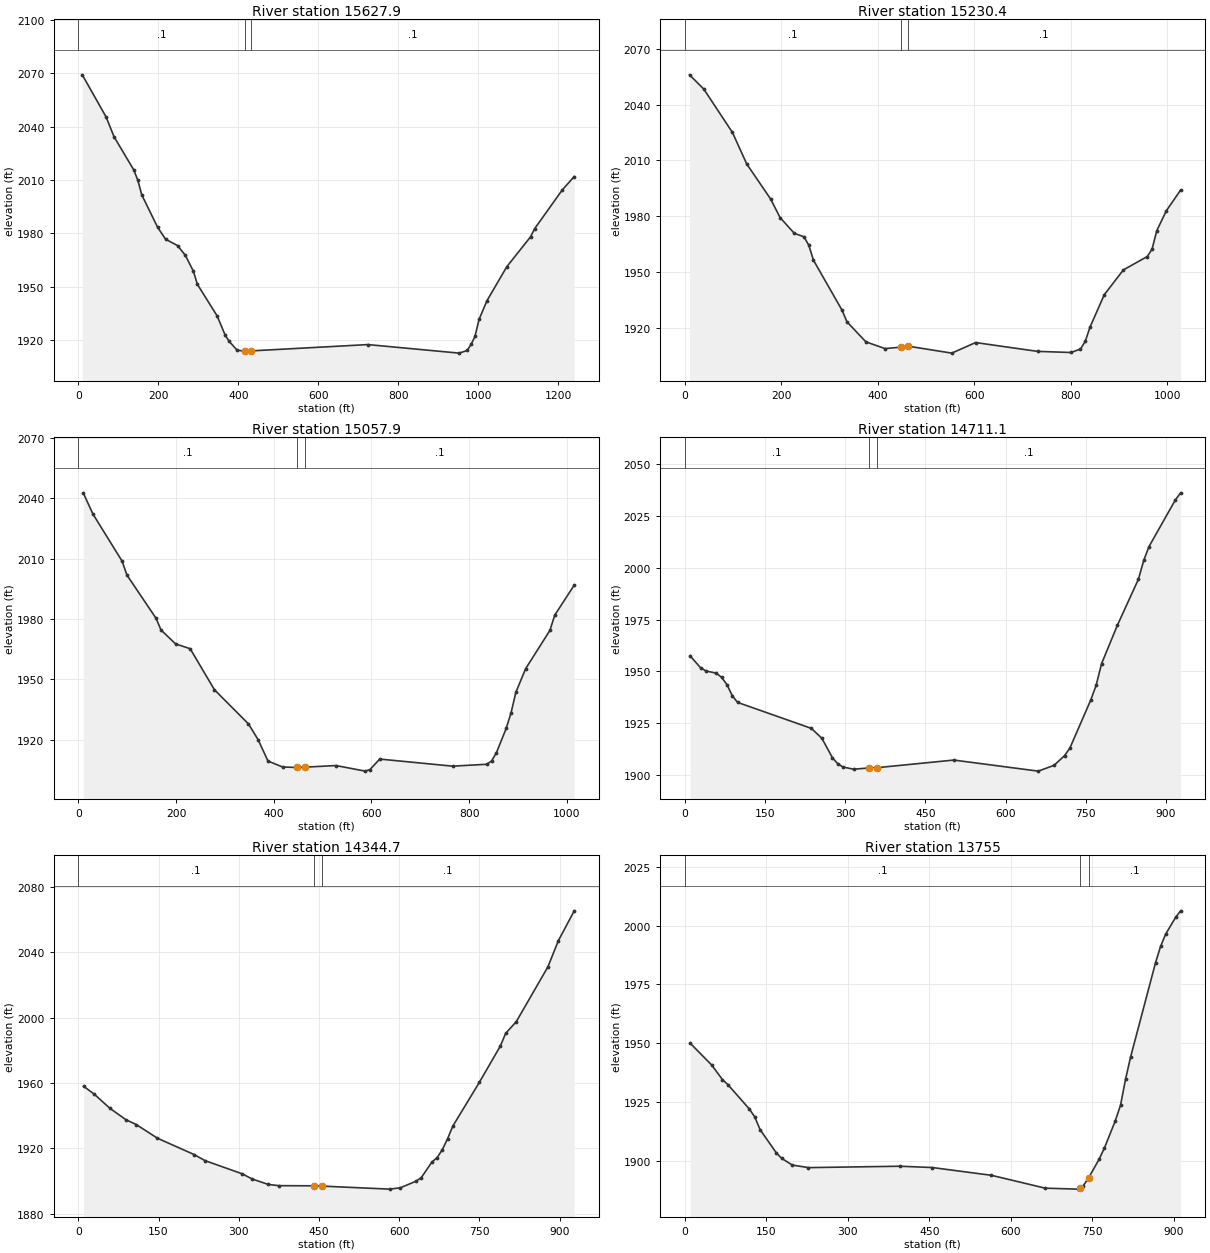
Type RM Length L Ch R = 1 ,15627.9 ,401.1,397.5,393.9
XS GIS Cut Line= 2
     2059438.444      312436.629     2060677.695      312457.319
#Sta/Elev= 30
     9.9 2069.23    69.4  2045.5    89.2 2034.38   138.8 2015.59   148.7 2009.85
   158.6  2001.6   198.3 1983.32   218.1 1976.67   247.9  1973.1   267.7 1967.53
   287.5 1958.67   297.5 1951.28     347 1933.45   366.9 1922.72   376.8 1919.21
   396.6 1914.24   416.9 1913.54   431.9 1913.79   723.8 1917.34   951.9 1912.53
   971.7 1914.02   981.6 1917.41   991.5 1922.02  1001.5 1931.49  1021.3 1942.04
  1070.9 1961.18  1130.4 1978.06  1140.3 1982.56  1209.7 2004.46  1239.4 2011.96
#Mann= 3 , 0 , 0
       0      .1       0   416.9    .045       0   431.9      .1       0
Bank Sta=416.9,431.9
XS Rating Curve= 0 ,0
Exp/Cntr=0.3,0.1

Type RM Length L Ch R = 1 ,15230.4 ,174.2,172.5,170.9
XS GIS Cut Line= 2
     2059532.084      312880.541     2060549.973      312736.797
#Sta/Elev= 30
     9.9 2056.02    39.5 2048.35    98.8 2025.05   128.5 2008.08   177.9 1989.25
   197.7  1979.2   227.3 1970.71   247.1  1968.9     257 1964.45   266.9 1956.26
   326.2 1929.33   336.1 1923.19   375.6 1912.33   415.1 1908.74   447.4 1909.47
   462.4 1910.06   553.5 1906.28     603 1911.97   731.5 1907.22   800.6 1906.62
   820.4 1908.49   830.3 1912.59   840.2 1920.32   869.8 1937.74   909.4 1951.07
   958.8 1958.25   968.7 1962.15   978.6 1972.19   998.3 1982.84    1028 1994.04
#Mann= 3 , 0 , 0
       0      .1       0   447.4    .045       0   462.4      .1       0
Bank Sta=447.4,462.4
XS Rating Curve= 0 ,0
Exp/Cntr=0.3,0.1

Type RM Length L Ch R = 1 ,15057.9 ,354.8,346.8,338.8
XS GIS Cut Line= 2
     2059548.559      313086.658     2060539.834      312868.609
#Sta/Elev= 30
      10 2042.75    29.9  2032.2    89.6 2008.75    99.5 2001.84   159.2 1980.29
   169.2 1974.53     199 1967.62   228.9 1965.22   278.6  1944.8   348.3 1927.81
   368.2 1919.88   388.1 1909.37   417.9  1906.4     448 1906.14     463 1906.29
   527.4 1907.11   587.1 1904.33     597 1905.13   616.9 1910.33   766.2  1906.8
   835.9 1907.74   845.8 1909.37   855.8  1913.5   875.7 1925.54   885.6  1933.2
   895.6 1943.56   915.5 1955.25   965.2 1974.31   975.2 1981.93    1015 1996.85
#Mann= 3 , 0 , 0
       0      .1       0     448    .045       0     463      .1       0
Bank Sta=448,463
XS Rating Curve= 0 ,0
Exp/Cntr=0.3,0.1

Type RM Length L Ch R = 1 ,14711.1 ,367.4,366.4,365.4
XS GIS Cut Line= 2
     2059834.694      313489.479     2060615.413      312989.048
#Sta/Elev= 30
     9.9 1957.56    29.6 1951.78    39.5 1950.26    59.2 1949.15    69.1 1947.13
    78.9 1943.65    88.8 1938.34    98.7 1935.08   236.8 1922.53   256.5 1917.72
   276.2 1908.36   286.1 1905.48     296 1903.88   315.7 1902.83   345.1 1903.44
   360.1 1903.58   503.1 1907.24     661  1901.9   690.6 1904.69   710.3  1909.4
   720.2 1913.02   759.6 1936.43   769.5 1943.46   779.4 1953.71     809 1972.26
   848.4 1994.52   858.3 2003.55   868.1 2010.24   917.5 2032.79   927.3  2036.2
#Mann= 3 , 0 , 0
       0      .1       0   345.1    .045       0   360.1      .1       0
Bank Sta=345.1,360.1
XS Rating Curve= 0 ,0
Exp/Cntr=0.3,0.1

Type RM Length L Ch R = 1 ,14344.7 ,582.4,589.7,597.1
XS GIS Cut Line= 2
     2060080.668      313786.389     2060795.959       313196.21
#Sta/Elev= 30
     9.9 1958.06    29.6 1953.28    59.2 1944.55    88.8 1937.64   108.5 1934.62
     148 1926.27     217 1916.21   236.8 1912.58   305.8 1904.57   325.6 1901.26
   355.2 1897.99   374.9 1897.24   440.5 1897.15   455.5 1896.97   582.1 1895.12
   601.8 1895.91   631.4 1899.95   641.2 1902.11     661 1911.61   670.8 1914.38
   680.7 1919.26   690.6 1926.08   700.4 1933.76   749.8 1960.43   789.2 1982.72
   799.1 1990.48   818.8 1997.54     878 2031.12   897.7  2047.2   927.3 2065.46
#Mann= 3 , 0 , 0
       0      .1       0   440.5    .045       0   455.5      .1       0
Bank Sta=440.5,455.5
XS Rating Curve= 0 ,0
Exp/Cntr=0.3,0.1

Type RM Length L Ch R = 1 ,13755   ,422.3,429.6,437.2
XS GIS Cut Line= 3
     2060190.026      313907.892     2060959.084      313681.698
     2061040.633      313607.242
#Sta/Elev= 30
     9.9 1950.02    49.5 1940.74    69.3 1934.54    79.2 1932.43   118.8 1922.03
   128.7 1918.67   138.6 1913.24   168.2 1903.43   178.1 1901.05   197.9 1898.17
   227.6 1897.08   395.9 1897.67   455.2 1897.12   564.1 1893.81   663.1 1888.34
   722.5 1887.93   727.8 1888.58   732.4 1889.14   742.8  1892.7     762 1900.57
   771.9 1905.41   791.7 1916.84   801.6 1923.63   810.8 1934.67     820 1944.05
     866 1984.27   875.2 1991.13   884.5 1996.37   902.9 2003.53   912.1  2006.3
#Mann= 3 , 0 , 0
       0      .1       0   727.8    .045       0   742.8      .1       0
Bank Sta=727.8,742.8
XS Rating Curve= 0 ,0
Exp/Cntr=0.3,0.1

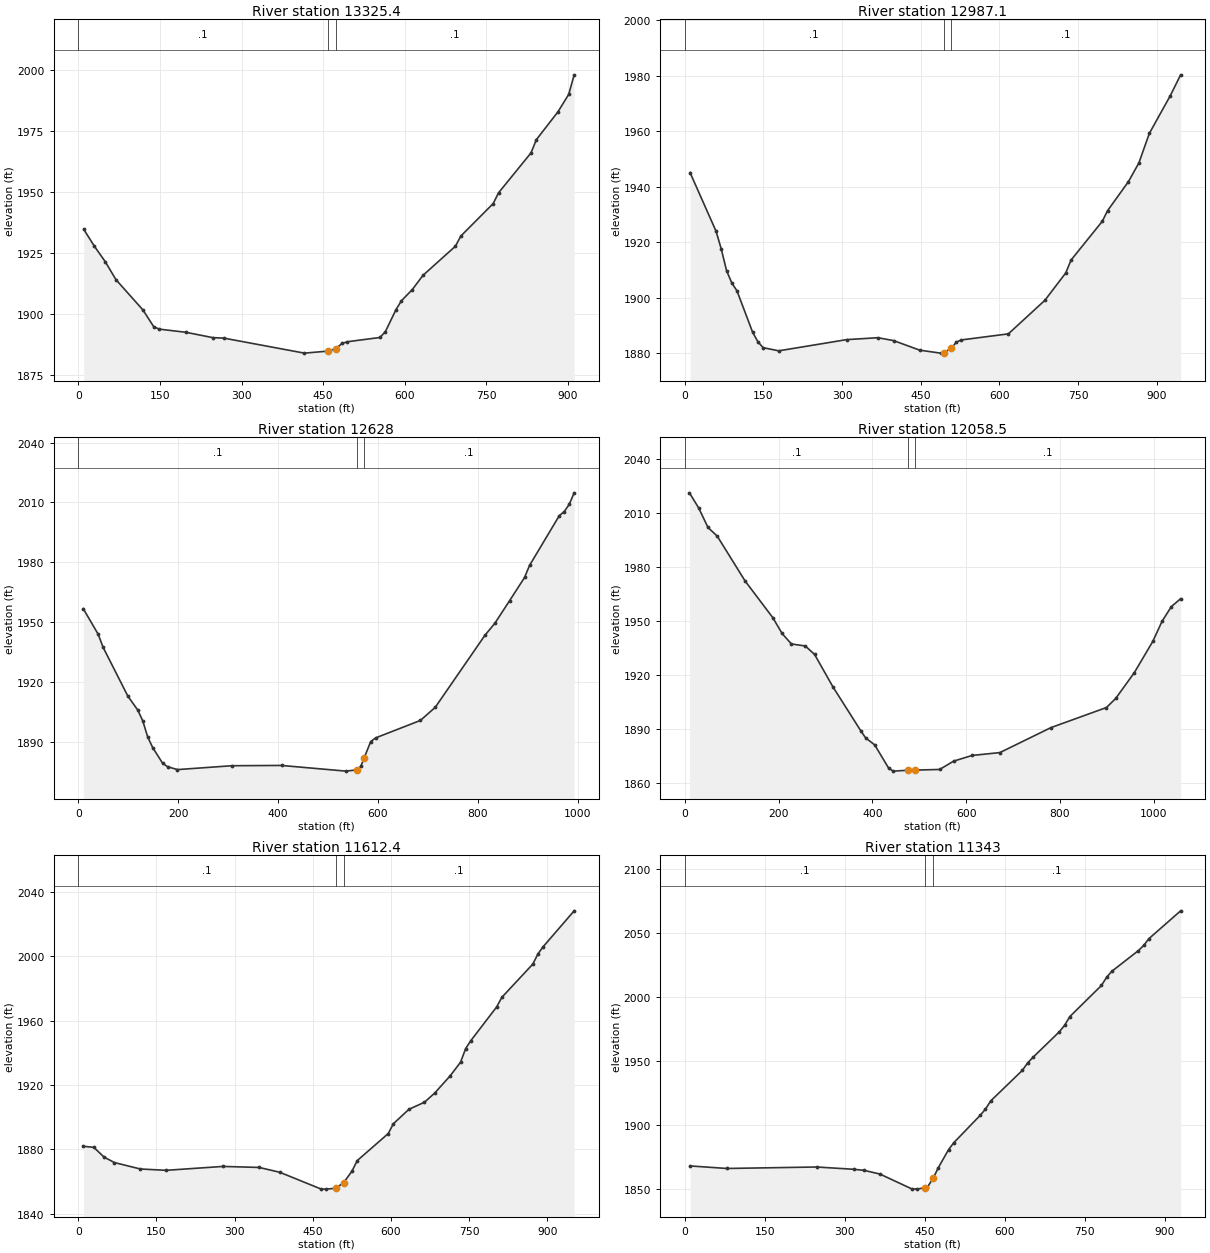
Type RM Length L Ch R = 1 ,13325.4 ,331.6,338.3,344.6
XS GIS Cut Line= 3
     2060325.604      314110.302     2060780.643      314112.552
     2061236.718      314129.658
#Sta/Elev= 30
     9.9 1934.68    29.7 1927.71    49.5 1921.43    69.2 1914.06   118.7 1901.68
   138.5 1894.84   148.4 1893.82   197.8 1892.51   247.3 1890.32   267.1 1890.14
   415.5 1883.98   458.2 1884.79   473.2 1885.82   484.8 1887.95   494.7 1888.65
   554.3 1890.39   564.2  1892.7     584 1901.83   593.9 1905.43   613.8 1909.99
   633.6 1915.86   693.2 1927.78   703.1 1931.94   762.6 1945.25   772.5 1949.67
   832.1    1966     842 1971.44   881.7 1982.84   901.5 1990.01   911.4 1997.97
#Mann= 3 , 0 , 0
       0      .1       0   458.2    .045       0   473.2      .1       0
Bank Sta=458.2,473.2
XS Rating Curve= 0 ,0
Exp/Cntr=0.3,0.1

Type RM Length L Ch R = 1 ,12987.1 ,351.8,359.1,366.1
XS GIS Cut Line= 2
      2060308.68      314293.415     2061207.879      314585.987
#Sta/Elev= 30
      10 1945.07    59.7  1923.9    69.7 1917.43    79.6 1909.76    89.6 1905.31
    99.5 1902.47   129.4 1887.54   139.4 1884.15   149.3 1882.01   179.2 1880.87
   308.6  1884.9   368.3 1885.59   398.1 1884.56   447.9 1881.11   487.7 1880.04
   493.5 1880.22   508.5 1881.73   517.6    1884   527.5 1884.79   617.1 1886.98
   686.8 1899.08   726.6 1908.94   736.6 1913.55   796.3 1927.54   806.2 1931.32
   846.1  1941.8     866 1948.53   885.9 1959.15   925.7 1972.68   945.6 1980.26
#Mann= 3 , 0 , 0
       0      .1       0   493.5    .045       0   508.5      .1       0
Bank Sta=493.5,508.5
XS Rating Curve= 0 ,0
Exp/Cntr=0.3,0.1

Type RM Length L Ch R = 1 ,12628   ,572,569.5,567.3
XS GIS Cut Line= 3
     2060199.415      314430.644     2060643.842      314764.277
     2060999.466      315018.635
#Sta/Elev= 30
     9.9 1956.65    39.7 1943.84    49.6 1937.27    99.2 1912.77   119.1 1905.75
     129 1900.38   138.9  1892.3   148.9 1886.96   168.7 1879.14   178.6 1877.38
   198.5 1875.92   307.6 1877.86   406.9    1878   535.9 1875.15   557.6 1875.77
   565.7 1877.56   572.6 1881.95   585.5 1889.98   595.5 1891.84   684.9 1900.57
   714.7 1907.15   814.1 1943.26     834 1949.29   863.8 1960.74   893.6 1972.31
   903.5 1978.33   963.1 2003.31   973.1 2005.41     983 2009.01   992.9 2014.78
#Mann= 3 , 0 , 0
       0      .1       0   557.6    .045       0   572.6      .1       0
Bank Sta=557.6,572.6
XS Rating Curve= 0 ,0
Exp/Cntr=0.3,0.1

Type RM Length L Ch R = 1 ,12058.5 ,456.6,446.1,435.5
XS GIS Cut Line= 2
     2059695.162      314656.897     2060607.304      315191.608
#Sta/Elev= 30
     9.9 2021.43    29.6 2013.03    49.4 2002.21    69.2 1997.37   128.5  1972.5
   187.7 1952.08   207.5 1943.31   227.3 1937.48   256.9 1936.38   276.7  1931.7
   316.2 1913.52   375.5 1889.17   385.4 1885.39   405.1 1881.38   434.8 1868.47
   444.7 1866.86   476.9 1867.37   491.9 1867.44   543.5 1867.79   573.1  1872.4
   612.7 1875.57   671.9 1877.16   780.6 1891.01   899.2 1902.19     919 1907.27
   958.5 1921.54     998 1938.93  1017.8 1950.12  1037.6 1958.25  1057.3 1962.62
#Mann= 3 , 0 , 0
       0      .1       0   476.9    .045       0   491.9      .1       0
Bank Sta=476.9,491.9
XS Rating Curve= 0 ,0
Exp/Cntr=0.3,0.1

Type RM Length L Ch R = 1 ,11612.4 ,263.2,269.4,275.6
XS GIS Cut Line= 2
     2059678.339      315280.388     2060627.339      315351.839
#Sta/Elev= 30
     9.9 1881.99    29.7 1881.33    49.6 1875.22    69.4 1871.88     119 1867.89
   168.5 1867.06   277.6 1869.48     347 1868.85   386.6 1865.86   465.9 1855.44
   475.8 1855.38   494.1 1855.92   509.1 1859.33   525.4 1866.63   535.3  1873.1
   594.8 1889.88   604.7    1896   634.5 1904.95   664.2 1909.33     684 1915.04
   713.8 1925.79   733.6  1934.2   743.5 1942.72   753.4 1947.63     803 1968.58
   812.9 1974.53   872.4 1995.19   882.3 2001.55   892.2 2005.97   951.7 2028.26
#Mann= 3 , 0 , 0
       0      .1       0   494.1    .045       0   509.1      .1       0
Bank Sta=494.1,509.1
XS Rating Curve= 0 ,0
Exp/Cntr=0.3,0.1

Type RM Length L Ch R = 1 ,11343   ,262.9,273.7,284
XS GIS Cut Line= 2
     2059664.663       315413.09     2060537.952      315731.636
#Sta/Elev= 30
     9.9 1867.73    79.1 1865.75   247.2  1866.9   316.5 1865.12   336.2 1864.28
   365.9 1861.37   425.2 1849.87   435.1 1849.61     451 1850.74   454.9 1851.25
     466 1858.24   474.7 1865.92   494.5 1880.44   504.3 1885.87   553.8 1907.26
   563.7 1912.14   573.6 1918.56   632.9 1942.43   642.8 1948.24   652.7 1952.56
   702.1 1972.51     712 1977.55   721.9 1984.44   781.2 2008.76   791.1 2015.31
     801 2019.94   850.5 2036.01   860.3 2039.98   870.2 2045.33   929.6 2067.06
#Mann= 3 , 0 , 0
       0      .1       0     451    .045       0     466      .1       0
Bank Sta=451,466
XS Rating Curve= 0 ,0
Exp/Cntr=0.3,0.1

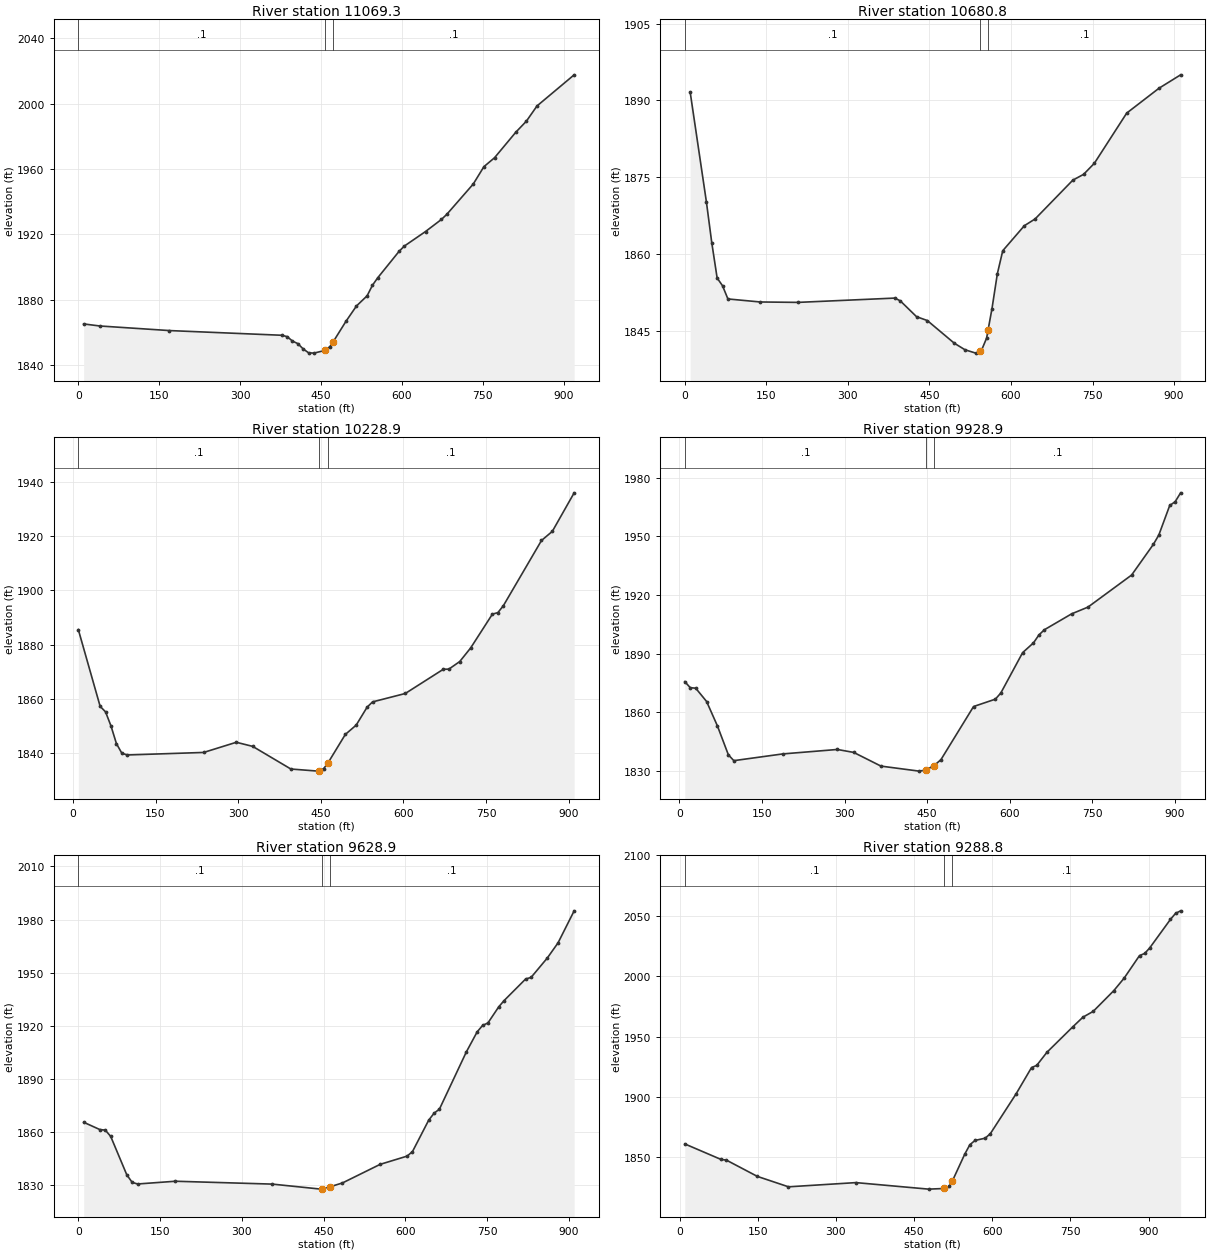
Type RM Length L Ch R = 1 ,11069.3 ,381.6,388.5,396
XS GIS Cut Line= 3
     2059611.998      315434.811     2059927.078      315779.084
     2060241.012      316105.576
#Sta/Elev= 30
     9.9 1865.04    39.7 1863.79   168.8 1860.98   377.3  1858.1   387.3 1857.27
   397.2 1854.54   407.1 1852.98     417 1849.74     427 1847.37   436.9 1847.16
   457.8 1848.85   466.7 1851.19   472.8 1854.17   496.2 1866.56   515.9 1876.05
   535.6 1882.26   545.5 1888.73   555.3 1893.31   594.7 1909.43   604.5  1912.7
   643.9 1921.63   673.5 1929.06   683.3 1932.14   732.5 1950.76   752.2 1961.36
   771.9 1966.82   811.3 1982.44     831 1989.23   850.7 1998.56   919.6 2017.62
#Mann= 3 , 0 , 0
       0      .1       0   457.8    .045       0   472.8      .1       0
Bank Sta=457.8,472.8
XS Rating Curve= 0 ,0
Exp/Cntr=0.3,0.1

Type RM Length L Ch R = 1 ,10680.8 ,446.7,451.9,457.1
XS GIS Cut Line= 2
     2059398.147      315515.874     2059782.413      316343.028
#Sta/Elev= 30
     9.9 1891.61    39.7 1870.23    49.6 1862.24    59.5 1855.34    69.4 1853.84
    79.3 1851.26   138.8 1850.67   208.2 1850.59   386.6 1851.43   396.5 1850.88
   426.3  1847.8   446.1 1847.05   495.7 1842.63   515.5 1841.34   535.3 1840.69
     543 1841.01   545.3 1841.11   555.2 1843.62     558 1845.25   565.1 1849.38
     575  1856.2   584.9 1860.67   624.6 1865.55   644.4 1866.87   713.8 1874.44
   733.6 1875.57   753.4 1877.73   812.9 1887.52   872.4 1892.38   912.1 1894.99
#Mann= 3 , 0 , 0
       0      .1       0     543    .045       0     558      .1       0
Bank Sta=543,558
XS Rating Curve= 0 ,0
Exp/Cntr=0.3,0.1

Type RM Length L Ch R = 1 ,10228.9 ,295.9,300,304.1
XS GIS Cut Line= 3
     2059111.493      315696.726     2059202.443      316142.543
     2059293.392      316588.361
#Sta/Elev= 30
     9.9 1885.56    49.5 1857.27    59.3 1855.24    69.2 1850.03    79.1  1843.5
      89 1839.95    98.9 1839.34   237.4 1840.27   296.7 1844.02   326.4 1842.51
   395.7 1834.16   445.1 1833.38   447.5 1833.59     455 1834.25   462.5  1836.2
   494.6 1846.91   514.3 1850.35   534.1 1856.96     544 1858.91   603.4 1862.01
   672.6 1870.96   682.5 1870.99   702.3  1873.8   722.1 1878.81   761.6 1891.29
   771.5 1891.83   781.4 1894.36   850.7 1918.44   870.4 1921.82     910 1936.02
#Mann= 3 , 0 , 0
     9.9      .1       0   447.5    .045       0   462.5      .1       0
#XS Ineff= 2 , 0
          296.72  1843.6
Permanent Ineff=
       F       F
Bank Sta=447.5,462.5
XS Rating Curve= 0 ,0
Exp/Cntr=0.3,0.1

Type RM Length L Ch R = 1 ,9928.9  ,298.9,300,300.9
XS GIS Cut Line= 3
     2058899.974      315736.931     2058907.555      316191.868
     2058915.135      316646.805
#Sta/Elev= 30
     9.9 1875.67    19.8 1872.57    29.7 1872.32    49.5  1865.5    69.2 1852.96
      89 1838.22    98.9 1835.24   187.9 1838.69   286.8 1840.96   316.5 1839.46
     366 1832.45   435.2 1829.88   447.5 1830.42   462.5 1832.75   474.8 1835.71
   534.1 1862.93   573.7  1866.7   583.6 1869.86   623.2 1890.51   642.9 1895.51
   652.8 1899.56   662.7 1902.22   712.2 1910.36   741.8  1913.8     821  1930.2
   860.5 1945.89   870.4 1950.67   890.2 1965.79   900.1 1967.73     910 1972.27
#Mann= 3 , 0 , 0
     9.9      .1       0   447.5    .045       0   462.5      .1       0
#XS Ineff= 2 , 0
          286.98 1840.91
Permanent Ineff=
       F       F
Bank Sta=447.5,462.5
XS Rating Curve= 0 ,0
Exp/Cntr=0.3,0.1

Type RM Length L Ch R = 1 ,9628.9  ,330.3,340.1,352.1
XS GIS Cut Line= 3
     2058623.282      315726.003      2058607.99      316180.776
     2058597.453      316635.649
#Sta/Elev= 30
     9.9 1865.62    39.6 1861.49    49.5  1861.2    59.4 1857.65      89 1835.94
    98.9  1831.7   108.8 1830.81   178.1 1832.36   356.1 1830.74   445.1 1827.91
   447.5 1827.99   462.5  1829.3   484.7 1831.39   553.9 1841.88   603.4 1846.53
   613.3  1849.1     643 1866.79   652.9 1870.74   662.7 1873.02   712.2 1905.35
     732 1916.63   741.9 1920.23   751.8 1921.67   771.5  1930.7   781.4 1934.27
     821 1946.46   830.9 1947.33   860.6 1958.24   880.4 1966.82     910  1984.9
#Mann= 3 , 0 , 0
       0      .1       0   447.5    .045       0   462.5      .1       0
Bank Sta=447.5,462.5
XS Rating Curve= 0 ,0
Exp/Cntr=0.3,0.1

Type RM Length L Ch R = 1 ,9288.8  ,493,497.9,500.8
XS GIS Cut Line= 3
     2058506.198      315696.211     2058281.379       316162.39
     2058050.589      316541.647
#Sta/Elev= 30
      10 1861.14    79.6 1848.29    89.6  1847.8   149.3 1834.27     209 1825.66
   338.4 1829.14   477.7 1823.75   508.2 1824.27   517.6 1826.06   523.2 1830.23
   547.2 1852.64     557 1860.46   566.9 1864.02   586.6 1865.91   596.5 1869.72
   645.8 1902.59   675.4 1924.32   685.3 1926.09     705 1936.97   754.3 1957.88
   774.1    1966   793.8 1970.81   833.3 1987.95     853 1998.22   882.6 2016.94
   892.5 2018.68   902.3 2023.34   941.8 2046.79   951.7 2051.82   961.5 2053.96
#Mann= 3 , 0 , 0
      10      .1       0   508.2    .045       0   523.2      .1       0
#XS Ineff= 2 , 0
          338.14 1829.07
Permanent Ineff=
       F       F
Bank Sta=508.2,523.2
XS Rating Curve= 0 ,0
Exp/Cntr=0.3,0.1