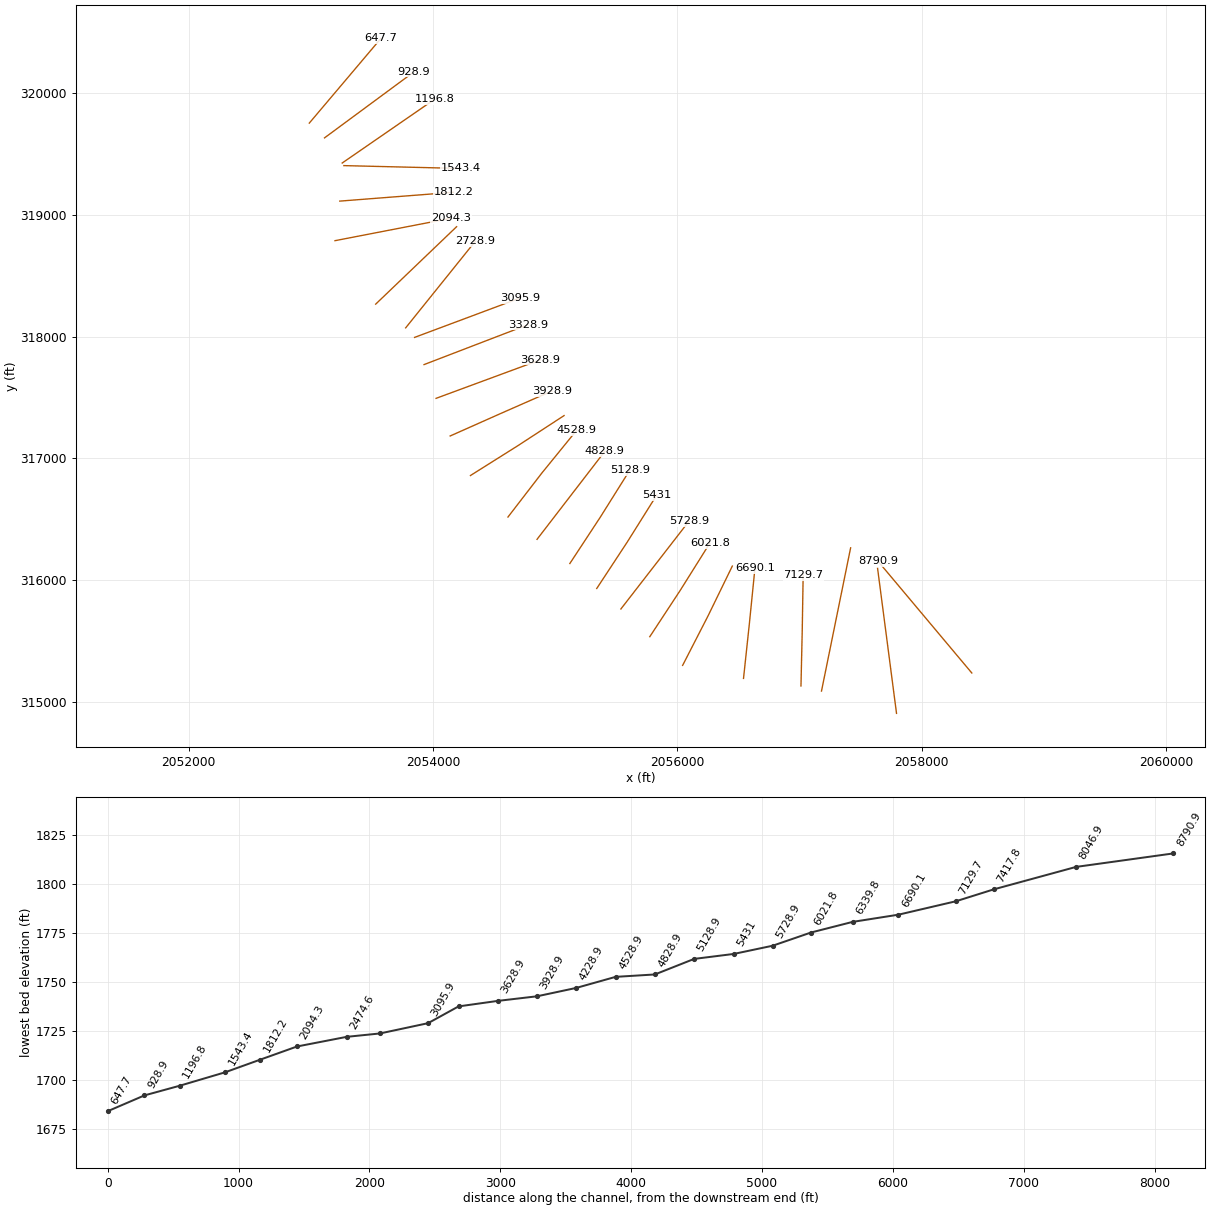
HEC-RAS study ABRMCRK.prj: ABRMCRK

--- ABRMCRK.g01 (geometry) --- (continued)

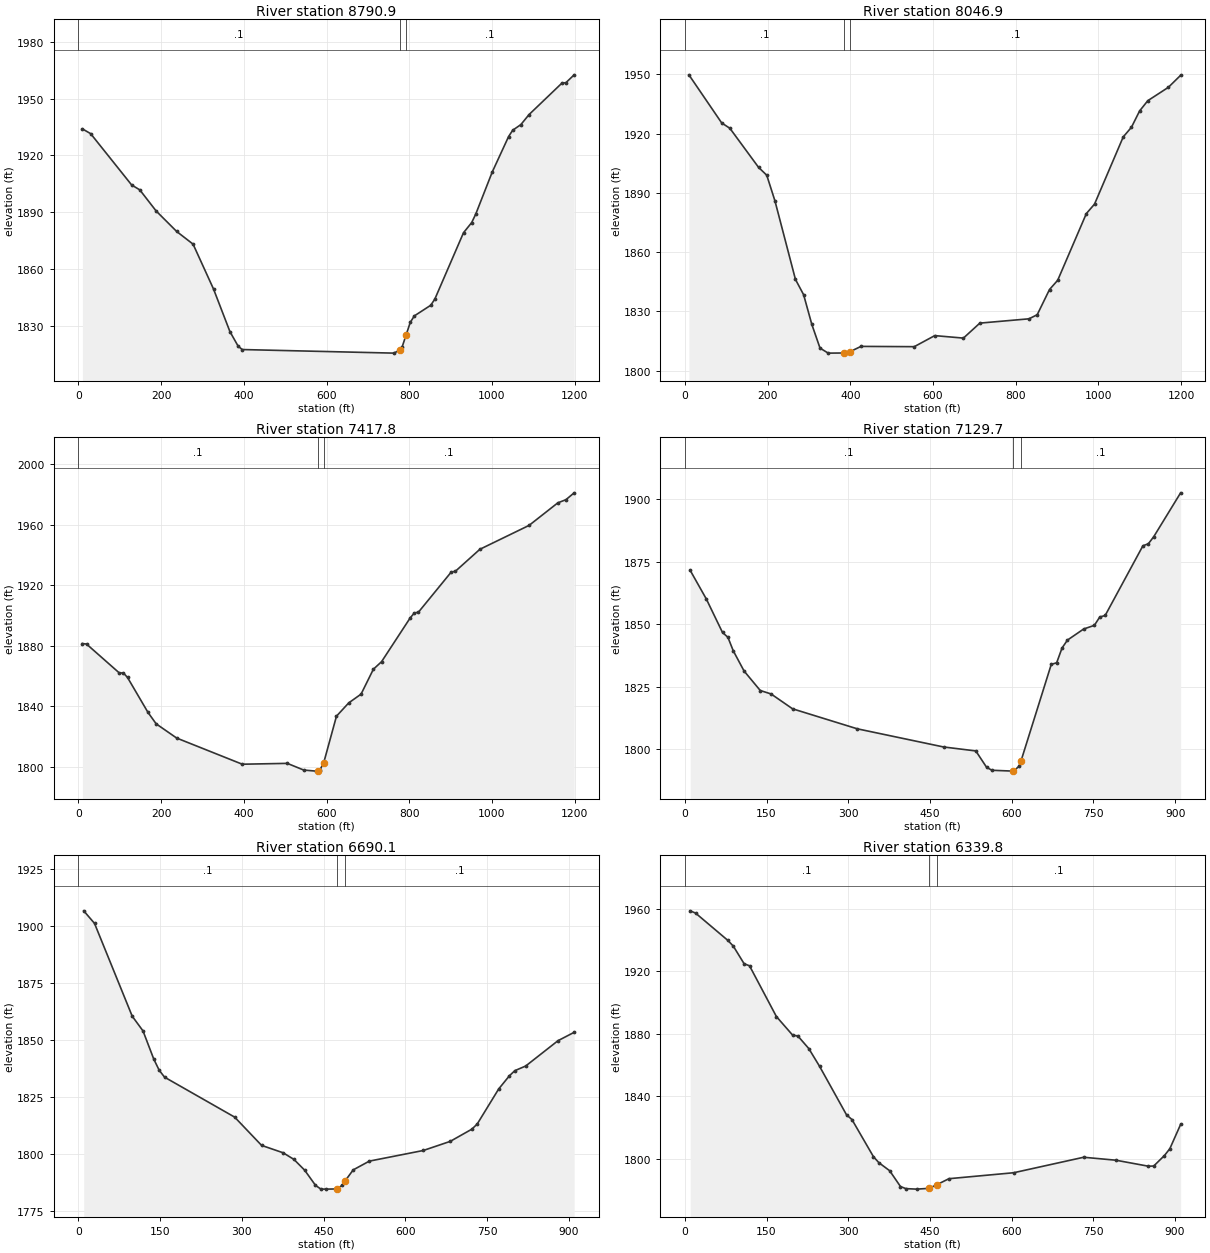
Type RM Length L Ch R = 1 ,8790.9  ,756.5,744.1,731.5
XS GIS Cut Line= 2
     2058409.274      315240.345     2057639.787      316159.441
#Sta/Elev= 30
     9.9 1934.01    29.7 1931.53   128.8 1904.46   148.6 1901.84   188.2 1890.69
   237.8 1879.89   277.4 1873.21   326.9  1849.5   366.5 1827.06   386.4 1819.36
   396.3  1817.6   762.8 1815.71   777.5 1817.34   782.6 1818.84   792.5 1825.32
   802.4  1831.9   812.3 1835.35     852 1840.97   861.9 1844.24   931.2 1879.24
     951  1884.6   960.9 1889.13  1000.6 1911.24  1040.2 1929.98  1050.1 1933.31
  1069.9  1936.3  1089.7 1941.59    1169 1958.15  1178.9 1958.44  1198.7 1962.55
#Mann= 3 , 0 , 0
       0      .1       0   777.5    .045       0   792.5      .1       0
Bank Sta=777.5,792.5
XS Rating Curve= 0 ,0
Exp/Cntr=0.3,0.1

Type RM Length L Ch R = 1 ,8046.9  ,636.4,629.1,621.8
XS GIS Cut Line= 2
     2057793.092      314909.261     2057638.256      316097.904
#Sta/Elev= 30
     9.9 1949.78    89.2 1925.41     109  1922.7   178.3 1902.92   198.1 1898.94
   217.9 1885.96   267.5 1846.17   287.3 1838.38   307.1 1823.37   326.9 1811.37
   346.7 1808.82   385.1 1808.89   400.1 1809.63     426 1812.23   554.8 1812.09
   604.3 1817.69   673.6 1816.43   713.3 1824.02   832.1  1826.2     852 1828.27
   881.7 1841.03   901.5 1845.72   970.8 1879.51   990.6 1884.31    1060 1918.35
  1079.8 1923.21  1099.6 1931.51  1119.4 1936.69    1169 1943.44  1198.7 1949.54
#Mann= 3 , 0 , 0
       0      .1       0   385.1    .045       0   400.1      .1       0
Bank Sta=385.1,400.1
XS Rating Curve= 0 ,0
Exp/Cntr=0.3,0.1

Type RM Length L Ch R = 1 ,7417.8  ,284.2,288.1,291.9
XS GIS Cut Line= 2
     2057179.076      315092.042     2057417.477      316266.781
#Sta/Elev= 30
     9.9 1881.52    19.8 1881.19    99.1 1862.12     109 1862.13   118.9 1859.14
   168.4 1836.09   188.2 1828.55   237.8 1819.17   396.3 1801.92   505.2 1802.48
   544.9 1798.07   574.6 1797.36   578.4 1797.73   584.5 1798.31   593.4 1803.05
   624.1 1833.62   653.8  1842.4   683.5 1848.15   713.3 1864.58   733.1 1869.56
   802.4 1898.49   812.3 1901.69   822.2  1902.2   901.5 1928.69   911.4 1929.17
   970.8 1943.72  1089.7 1959.47  1159.1 1974.33  1178.9 1976.45  1198.7 1980.96
#Mann= 3 , 0 , 0
       0      .1       0   578.4    .045       0   593.4      .1       0
Bank Sta=578.4,593.4
XS Rating Curve= 0 ,0
Exp/Cntr=0.3,0.1

Type RM Length L Ch R = 1 ,7129.7  ,441.7,439.6,437.4
XS GIS Cut Line= 3
     2057011.168      315133.981      2057021.52      315588.874
     2057029.061       316043.81
#Sta/Elev= 30
     9.9 1871.47    39.6    1860    69.2 1846.67    79.1 1844.76      89 1839.33
   108.8 1831.28   138.5  1823.5   158.3 1822.13   197.8 1816.19   316.5 1808.21
   474.8 1800.96   534.1 1799.37   553.9 1792.83   563.8 1791.65     602 1791.32
   603.4 1791.31   613.3 1793.25     617 1795.33   672.6 1833.93   682.5 1834.58
   692.4 1840.49   702.3 1843.63     732 1848.05   751.7 1849.52   761.6 1852.85
   771.5 1853.45   840.8 1881.29   850.7 1882.08   860.6 1884.89     910 1902.43
#Mann= 3 , 0 , 0
       0      .1       0     602    .045       0     617      .1       0
Bank Sta=602,617
XS Rating Curve= 0 ,0
Exp/Cntr=0.3,0.1

Type RM Length L Ch R = 1 ,6690.1  ,358.4,350.3,342.6
XS GIS Cut Line= 3
     2056540.943      315196.106     2056589.209       315648.55
     2056634.679       316101.27
#Sta/Elev= 30
     9.9 1906.46    29.7 1900.95    98.9 1860.26   118.7 1853.81   138.5 1841.43
   148.4 1836.57   158.3 1833.53   286.9 1816.02   336.3 1803.63   375.9 1800.38
   395.7 1797.48   415.4 1792.75   435.2 1786.14   445.1 1784.46     455 1784.45
   473.9 1784.53   484.7 1786.14   488.9 1787.83   504.5 1792.89   534.1 1796.73
   633.1 1801.39   682.5 1805.38   722.1 1810.72     732 1812.97   771.5 1828.37
   791.3 1834.18   801.2  1836.4     821 1838.41   880.3 1849.52     910  1853.2
#Mann= 3 , 0 , 0
       0      .1       0   473.9    .045       0   488.9      .1       0
Bank Sta=473.9,488.9
XS Rating Curve= 0 ,0
Exp/Cntr=0.3,0.1

Type RM Length L Ch R = 1 ,6339.8  ,319.9,318,316
XS GIS Cut Line= 3
     2056042.706      315302.994     2056250.328      315708.126
     2056449.332      316117.274
#Sta/Elev= 30
     9.9 1958.69    19.8 1957.23    79.2 1939.74    89.1  1936.1   108.9 1924.86
   118.8 1923.56   168.2 1891.08   197.9 1879.24   207.8 1878.57   227.6 1870.64
   247.4 1859.28   296.9 1828.26   306.8 1825.27   346.4 1801.47   356.3 1797.66
   376.1 1792.53   395.9 1782.44   405.8 1781.09   425.5 1780.77   448.3 1781.26
   463.3 1783.72   484.9 1787.44   603.6 1791.24   732.2 1801.15   791.5 1799.25
   850.9 1795.43   860.8 1795.54   880.5 1802.25   890.4 1806.62   910.2 1822.16
#Mann= 3 , 0 , 0
       0      .1       0   448.3    .045       0   463.3      .1       0
Bank Sta=448.3,463.3
XS Rating Curve= 0 ,0
Exp/Cntr=0.3,0.1

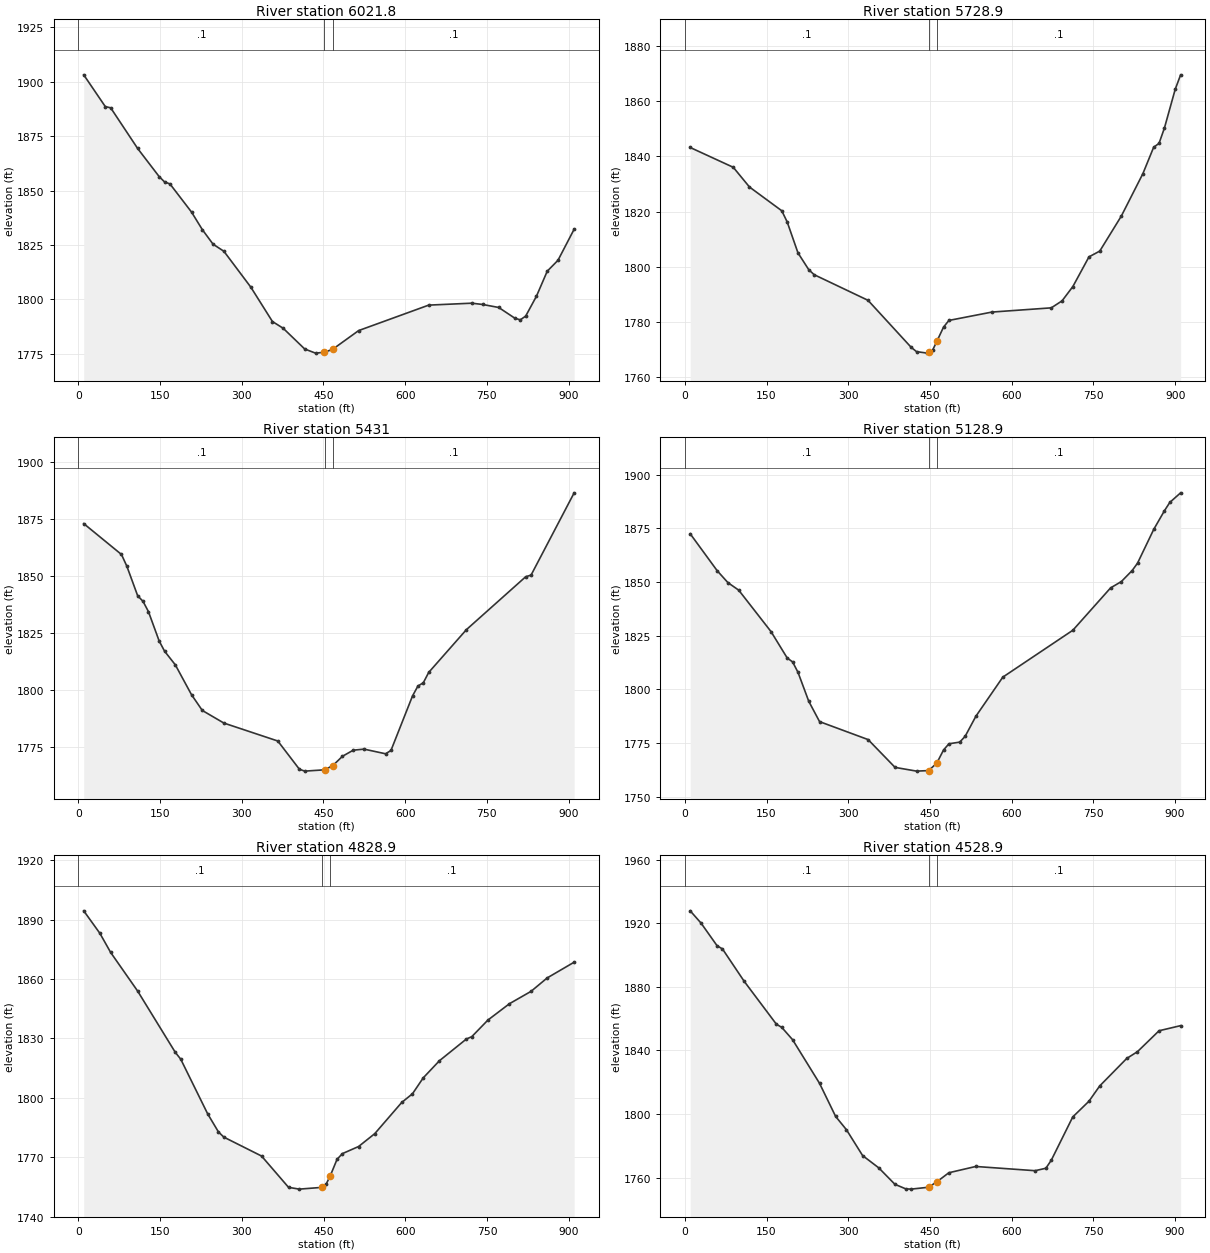
Type RM Length L Ch R = 1 ,6021.8  ,295.2,293,290.3
XS GIS Cut Line= 3
      2055773.94       315538.17     2056023.509      315918.898
     2056264.936      316304.537
#Sta/Elev= 30
     9.9 1903.18    49.5 1888.59    59.4 1888.02   108.9 1869.35   148.4 1856.43
   158.3 1853.99   168.2 1853.07   207.8 1840.14   227.6 1832.08   247.4 1825.37
   267.2 1822.14   316.7 1805.63   356.3 1789.87   376.1 1786.76   415.6 1777.24
   435.4 1775.35   451.7 1775.75   466.7 1777.08   514.6 1785.71   643.2  1797.4
   722.3 1798.29   742.1  1797.7   771.7 1796.32   801.4 1791.38   811.3 1790.64
   821.2 1792.35     841  1801.5   860.8 1812.99   880.5 1817.99   910.2 1832.29
#Mann= 3 , 0 , 0
       0      .1       0   451.7    .045       0   466.7      .1       0
Bank Sta=451.7,466.7
XS Rating Curve= 0 ,0
Exp/Cntr=0.3,0.1

Type RM Length L Ch R = 1 ,5728.9  ,295.6,297.9,300.7
XS GIS Cut Line= 3
     2055537.321      315765.365     2055815.803      316125.189
     2056094.284      316485.013
#Sta/Elev= 30
     9.9 1843.27      89 1836.07   118.7 1828.92     178 1820.29   187.9 1816.25
   207.7 1805.01   227.5  1798.9   237.4 1797.09   336.3 1787.78   415.4 1770.73
   425.3 1769.15   445.1 1768.61   447.5 1768.89     455 1769.78   462.5 1772.84
   474.8 1778.03   484.7 1780.48   563.8 1783.52   672.6 1785.05   692.4 1787.59
   712.2 1792.78   741.8 1803.56   761.6 1805.66   801.2 1818.38   840.8  1833.8
   860.5 1843.35   870.4 1844.77   880.3 1850.36   900.1 1864.42     910 1869.65
#Mann= 3 , 0 , 0
       0      .1       0   447.5    .045       0   462.5      .1       0
Bank Sta=447.5,462.5
XS Rating Curve= 0 ,0
Exp/Cntr=0.3,0.1

Type RM Length L Ch R = 1 ,5431    ,302.7,302.1,301.6
XS GIS Cut Line= 3
     2055339.979      315933.727     2055589.549      316314.454
     2055830.976      316700.094
#Sta/Elev= 30
     9.9 1872.99    79.2 1859.44    89.1 1854.28   108.9 1841.35   118.8 1838.87
   128.7 1834.38   148.4 1821.49   158.3 1817.03   178.1 1811.01   207.8 1797.92
   227.6 1791.02   267.2 1785.49   366.2 1777.62   405.8 1765.24   415.6 1764.41
     452 1764.98     467  1766.8   484.9 1770.93   504.7  1773.6   524.5 1774.06
     564 1772.02   573.9 1773.47   613.5 1797.41   623.4 1801.73   633.3 1803.18
   643.2 1807.71   712.4 1826.47   821.2 1849.67   831.1  1850.4   910.2 1886.49
#Mann= 3 , 0 , 0
       0      .1       0     452    .045       0     467      .1       0
Bank Sta=452,467
XS Rating Curve= 0 ,0
Exp/Cntr=0.3,0.1

Type RM Length L Ch R = 1 ,5128.9  ,301.7,300,297.8
XS GIS Cut Line= 3
     2055119.765       316138.38     2055369.334      316519.108
     2055610.761      316904.747
#Sta/Elev= 30
     9.9 1872.52    59.4 1855.31    79.2 1849.73      99 1846.23   158.3 1826.91
     188 1814.61   197.9 1812.79   207.8 1807.94   227.6 1794.41   247.4 1784.95
   336.5 1776.58     386 1763.62   425.5 1761.88   447.7 1762.14   462.7 1765.66
     475 1771.75   484.9 1774.63   504.7  1775.4   514.6 1778.09   534.4 1787.48
   583.8 1805.69   712.4 1827.56   781.6 1847.28   801.4 1850.24   821.2 1855.37
   831.1 1858.82   860.8 1874.54   880.5 1883.25   890.4 1887.15   910.2  1891.6
#Mann= 3 , 0 , 0
       0      .1       0   447.7    .045       0   462.7      .1       0
Bank Sta=447.7,462.7
XS Rating Curve= 0 ,0
Exp/Cntr=0.3,0.1

Type RM Length L Ch R = 1 ,4828.9  ,300,300,299.4
XS GIS Cut Line= 3
     2054851.174      316336.743     2055128.475      316697.477
     2055405.775      317058.211
#Sta/Elev= 30
     9.9 1894.42    39.6 1883.05    59.3 1873.43   108.8 1853.94     178 1822.97
   187.9 1819.56   237.4 1791.93   257.2  1782.8   267.1 1780.19   336.3 1770.65
   385.8 1754.85   405.5 1753.95   447.5 1754.84     455 1756.58   462.5 1760.75
   474.8 1768.99   484.7 1771.88   514.3 1775.45     544 1781.94   593.5 1797.69
   613.3 1802.09     633 1810.11   662.7 1818.75   712.2 1829.72   722.1  1830.9
   751.7 1839.28   791.3 1847.55   830.9 1853.78   860.5 1860.55     910  1868.5
#Mann= 3 , 0 , 0
       0      .1       0   447.5    .045       0   462.5      .1       0
Bank Sta=447.5,462.5
XS Rating Curve= 0 ,0
Exp/Cntr=0.3,0.1

Type RM Length L Ch R = 1 ,4528.9  ,308,300,293
XS GIS Cut Line= 3
     2054613.348      316519.605     2054890.628      316880.313
     2055177.539      317233.703
#Sta/Elev= 30
     9.9 1927.78    29.7 1920.12    59.3  1905.8    69.2 1903.79   108.8 1883.55
   168.1 1856.47     178 1854.46   197.8 1846.75   247.3  1819.3   276.9 1798.44
   296.7  1790.1   326.4 1773.84   356.1 1766.09   385.7 1755.76   405.5  1752.9
   415.4 1752.72   447.5 1753.91   462.5 1757.28   484.7 1763.02   534.1 1766.97
     643 1764.31   662.8 1765.85   672.7 1770.85   712.2 1798.13   741.9    1808
   761.7 1817.64   811.2  1834.9     831 1839.19   870.6 1852.34   910.2 1855.56
#Mann= 3 , 0 , 0
       0      .1       0   447.5    .045       0   462.5      .1       0
Bank Sta=447.5,462.5
XS Rating Curve= 0 ,0
Exp/Cntr=0.3,0.1

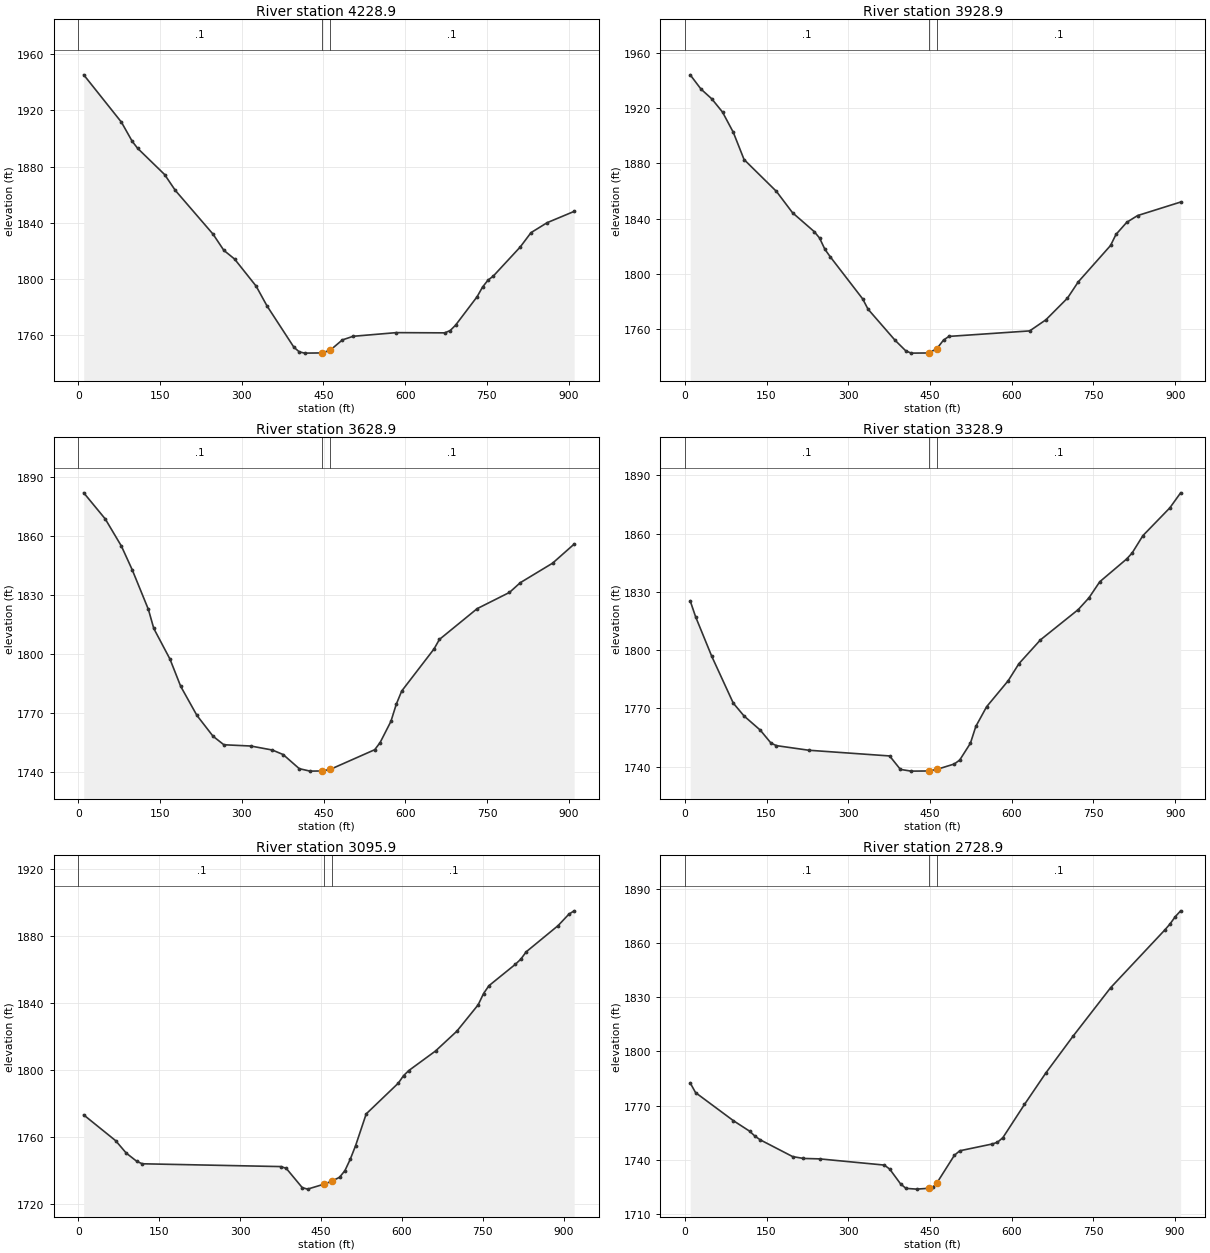
Type RM Length L Ch R = 1 ,4228.9  ,303.2,300,296.3
XS GIS Cut Line= 3
      2054306.37      316860.062     2054691.278      317102.672
     2055072.315       317351.47
#Sta/Elev= 30
     9.9 1945.32    79.1  1911.6    98.9 1897.96   108.8    1893   158.3 1874.32
     178 1863.01   247.3 1831.82   267.1  1820.3   286.8 1814.11   326.4 1794.79
   346.2  1780.8   395.6 1751.34   405.5    1748   415.4 1747.09   447.5 1747.24
   462.5 1749.25   484.7 1756.52   504.5 1759.09   583.6 1761.69   672.6 1761.53
   682.5 1763.16   692.4 1766.99     732 1787.29   741.9 1794.12   751.8 1799.01
   761.7 1801.99   811.1 1822.69   830.9 1832.91   860.6 1840.02   910.1 1848.05
#Mann= 3 , 0 , 0
       0      .1       0   447.5    .045       0   462.5      .1       0
Bank Sta=447.5,462.5
XS Rating Curve= 0 ,0
Exp/Cntr=0.3,0.1

Type RM Length L Ch R = 1 ,3928.9  ,301.5,300,298.6
XS GIS Cut Line= 3
     2054140.128      317184.188     2054555.683      317369.493
     2054972.066      317552.947
#Sta/Elev= 30
     9.9  1943.9    29.7  1933.6    49.5 1926.55    69.2 1916.99      89 1902.37
   108.8 1882.67   168.2 1859.66   197.8 1844.22   237.4 1830.66   247.3    1826
   257.2 1817.77   267.1 1812.35   326.4 1782.04   336.3 1774.58   385.8 1752.15
   405.5 1744.49   415.4 1742.81   447.5 1742.93   462.5 1745.99   474.8 1752.22
   484.7 1754.89     633 1758.87   662.7 1766.88   702.3 1782.54   722.1 1794.28
   781.4 1820.59   791.3 1828.54   811.1 1837.33   830.9 1842.19     910 1851.98
#Mann= 3 , 0 , 0
       0      .1       0   447.5    .045       0   462.5      .1       0
Bank Sta=447.5,462.5
XS Rating Curve= 0 ,0
Exp/Cntr=0.3,0.1

Type RM Length L Ch R = 1 ,3628.9  ,299.7,300,300.3
XS GIS Cut Line= 3
     2054024.979      317492.955     2054451.708       317650.84
     2054878.437      317808.725
#Sta/Elev= 30
     9.9 1881.78    49.5 1868.48    79.1  1854.7    98.9  1842.7   128.6 1822.56
   138.5 1812.89   168.2 1797.34   187.9  1783.5   217.6 1768.77   247.3 1758.16
   267.1 1753.85   316.5 1753.21   356.1 1751.17   375.9 1748.88   405.5 1741.71
   425.3 1740.46   447.5 1740.55   462.5 1741.37     544 1751.34   553.9 1754.99
   573.7 1765.73   583.6 1774.48   593.5 1781.14   652.8  1802.5   662.7 1807.33
     732 1822.97   791.3 1831.21   811.1 1836.14   870.4 1846.06     910 1855.75
#Mann= 3 , 0 , 0
       0      .1       0   447.5    .045       0   462.5      .1       0
Bank Sta=447.5,462.5
XS Rating Curve= 0 ,0
Exp/Cntr=0.3,0.1

Type RM Length L Ch R = 1 ,3328.9  ,233.2,233,232.8
XS GIS Cut Line= 3
     2053926.629      317769.844     2054351.286       317933.22
     2054775.943      318096.596
#Sta/Elev= 30
     9.9 1825.38    19.8 1817.19    49.5 1796.78      89 1772.67   108.8 1766.04
   138.5 1758.78   158.3 1752.06   168.2 1750.78   227.5 1748.41   375.9 1745.47
   395.7 1738.54   415.4 1737.65   447.5 1737.73   462.5 1738.53   494.6 1741.33
   504.5 1743.34   524.2 1752.02   534.1 1760.67   553.9 1770.81   593.5 1784.21
   613.3 1793.03   652.8 1805.28   722.1 1820.87   741.8 1826.93   761.6 1835.21
   811.1 1846.97     821 1850.02   840.8 1858.97   890.2 1873.27     910 1881.01
#Mann= 3 , 0 , 0
       0      .1       0   447.5    .045       0   462.5      .1       0
Bank Sta=447.5,462.5
XS Rating Curve= 0 ,0
Exp/Cntr=0.3,0.1

Type RM Length L Ch R = 1 ,3095.9  ,354.9,367,379.1
XS GIS Cut Line= 2
     2053848.712      317992.666     2054709.914      318315.039
#Sta/Elev= 30
     9.9 1773.35    69.2 1757.97      89 1750.53   108.8 1745.57   118.7  1744.2
   375.7 1742.53   385.6 1741.48   415.3 1729.98   425.2 1729.09   456.2 1732.11
   471.2 1734.01   484.5 1736.17   494.4  1740.1   504.3 1746.89   514.2 1754.97
   533.9 1773.94   593.3 1792.22   603.2 1796.74     613  1799.8   662.5 1811.44
     702 1823.23   741.6 1838.98   751.5 1845.63   761.4 1850.32   810.8 1863.17
   820.7  1866.2   830.6 1870.54   889.9  1886.2   909.7 1892.96   919.6 1894.99
#Mann= 3 , 0 , 0
       0      .1       0   456.2    .045       0   471.2      .1       0
Bank Sta=456.2,471.2
XS Rating Curve= 0 ,0
Exp/Cntr=0.3,0.1

Type RM Length L Ch R = 1 ,2728.9  ,257.2,254.3,251.4
XS GIS Cut Line= 3
     2053776.071      318071.031     2054061.054      318426.211
     2054345.762      318780.964
#Sta/Elev= 30
     9.9  1782.6    19.8 1777.21    89.1 1761.73   118.8 1755.94   128.7 1753.18
   138.6  1751.1     198 1741.84   217.8 1740.82   247.5 1740.58   366.3 1737.15
   376.2 1734.91     396 1726.79   405.9 1724.27   425.7 1723.85   447.9 1724.32
   455.4 1724.79   462.9 1727.34   494.9 1742.56   504.8 1745.06   564.2  1748.8
     574 1749.77   583.9 1752.32   623.5 1770.66     663  1788.2   712.5 1808.35
   781.7 1835.25   880.6 1867.01   890.5 1870.42   900.4 1874.55   910.2 1877.77
#Mann= 3 , 0 , 0
       0      .1       0   447.9    .045       0   462.9      .1       0
Bank Sta=447.9,462.9
XS Rating Curve= 0 ,0
Exp/Cntr=0.3,0.1

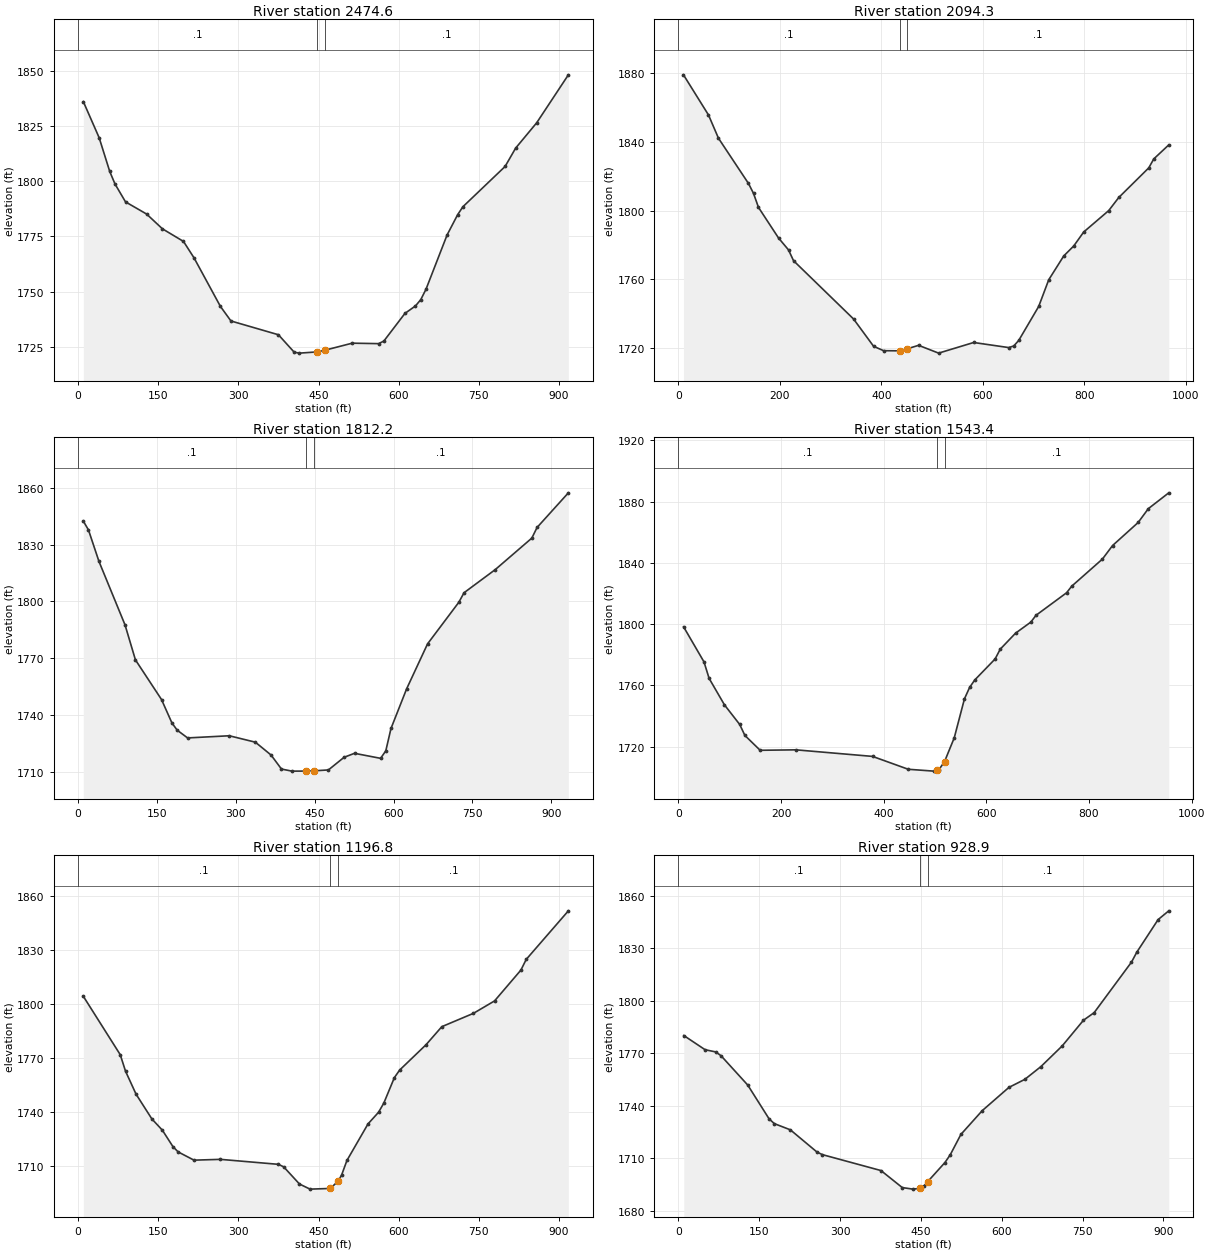
Type RM Length L Ch R = 1 ,2474.6  ,393.3,380.3,367.3
XS GIS Cut Line= 2
     2053530.673      318265.545     2054192.841      318900.611
#Sta/Elev= 30
     9.9 1836.09    39.5 1819.73    59.2 1804.51    69.1 1798.79    88.8 1790.67
   128.3 1785.15   157.8 1778.47   197.3 1772.74     217  1765.3   266.4 1743.29
   286.1 1736.69   374.9 1730.45   404.5 1722.53   414.3 1722.12   447.2 1722.67
   462.2 1723.46     513 1726.63   562.3 1726.42   572.2 1727.58   611.7 1740.13
   631.4 1743.51   641.3 1746.37   651.1 1751.08   690.6  1775.7   710.3 1784.86
   720.2 1788.48   799.1 1806.72   818.8 1815.02   858.3 1826.54   917.5 1848.25
#Mann= 3 , 0 , 0
       0      .1       0   447.2    .045       0   462.2      .1       0
Bank Sta=447.2,462.2
XS Rating Curve= 0 ,0
Exp/Cntr=0.3,0.1

Type RM Length L Ch R = 1 ,2094.3  ,283.3,282.1,280.9
XS GIS Cut Line= 2
     2053197.971      318786.043      2054147.12      318970.101
#Sta/Elev= 30
     9.9 1878.97    59.2 1855.64    78.9 1842.11   138.1  1815.8     148 1810.03
   157.8  1801.9   197.3 1784.13     217 1777.19   226.9 1770.92   345.3 1737.02
   384.8 1721.15   404.5 1718.61   436.1 1718.52   451.1 1719.71   473.5 1721.72
     513 1717.19   582.1 1723.37   651.1 1720.42     661 1721.32   670.9 1724.55
   710.3 1744.32   730.1 1759.83   759.7 1773.68   779.4 1779.47   799.1 1787.62
   848.4 1800.05   868.2 1807.66   927.4  1824.9   937.2 1830.08   966.8 1838.24
#Mann= 3 , 0 , 0
       0      .1       0   436.1    .045       0   451.1      .1       0
Bank Sta=436.1,451.1
XS Rating Curve= 0 ,0
Exp/Cntr=0.3,0.1

Type RM Length L Ch R = 1 ,1812.2  ,272.5,268.8,265.1
XS GIS Cut Line= 2
     2053236.654      319110.456     2054166.198      319182.929
#Sta/Elev= 30
     9.9 1842.43    19.8 1837.72    39.7 1821.15    89.3 1787.63   109.1 1769.16
   158.7 1748.23   178.5 1735.88   188.5 1732.06   208.3 1727.97   287.6 1729.11
   337.2 1725.72     367 1718.95   386.8 1711.55   406.7 1710.45   432.9 1710.47
   447.9 1710.59   476.1 1711.08   505.9 1717.75   525.7 1719.85   575.3  1717.2
   585.2 1721.15   595.1 1732.97   624.9 1753.92   664.6 1777.59   724.1 1799.56
     734 1804.58   793.5 1816.82   862.9 1833.41   872.9 1839.03   932.4  1857.3
#Mann= 3 , 0 , 0
       0      .1       0   432.9    .045       0   447.9      .1       0
Bank Sta=432.9,447.9
XS Rating Curve= 0 ,0
Exp/Cntr=0.3,0.1

Type RM Length L Ch R = 1 ,1543.4  ,332.4,346.5,360.7
XS GIS Cut Line= 2
     2053270.468      319401.654     2054225.567      319378.338
#Sta/Elev= 30
      10 1798.25    49.8 1775.31    59.7 1764.59    89.6 1747.29   119.4 1734.45
   129.4 1727.32   159.2  1717.6   228.9  1717.9   378.2 1713.61   447.8  1705.2
   497.6 1703.99   503.5 1704.55   507.5 1704.93   518.5 1710.25   537.4 1725.76
   557.3 1751.25   567.3 1758.65   577.2 1763.48     617 1777.26     627 1783.66
   656.8 1794.09   686.7 1801.37   696.6 1805.76   756.3 1820.51   766.3 1824.81
     826 1842.48   845.9 1851.36   895.7 1866.41   915.6 1875.46   955.4 1885.79
#Mann= 3 , 0 , 0
       0      .1       0   503.5    .045       0   518.5      .1       0
Bank Sta=503.5,518.5
XS Rating Curve= 0 ,0
Exp/Cntr=0.3,0.1

Type RM Length L Ch R = 1 ,1196.8  ,267.2,268,268.7
XS GIS Cut Line= 2
     2053256.402      319422.792     2054011.113      319944.503
#Sta/Elev= 30
     9.9 1804.12    78.9 1771.76    88.8 1762.62   108.5 1749.85   138.1  1736.1
   157.8 1729.83   177.6  1720.7   187.4 1717.77     217 1713.21   266.4 1713.66
   374.9  1710.9   384.8  1709.5   414.3 1699.98   434.1 1697.14   472.1 1697.51
   487.1 1701.71   493.3 1705.05   503.1 1713.03   542.6 1733.34   562.3 1739.79
   572.2 1744.91   591.9 1759.01   601.8 1763.22   651.1 1777.25   680.7 1787.29
   739.9 1794.69   779.4 1801.59   828.7  1818.7   838.6 1824.61   917.5 1851.57
#Mann= 3 , 0 , 0
       0      .1       0   472.1    .045       0   487.1      .1       0
Bank Sta=472.1,487.1
XS Rating Curve= 0 ,0
Exp/Cntr=0.3,0.1

Type RM Length L Ch R = 1 ,928.9   ,275.9,281.2,286.4
XS GIS Cut Line= 3
     2053111.789      319629.007     2053477.597      319899.578
     2053843.406       320170.15
#Sta/Elev= 30
     9.9 1780.14    49.5    1772    69.2 1770.76    79.1 1768.55   128.6 1751.78
   168.2 1732.45     178 1729.71   207.7 1726.17   257.2 1713.43   267.1 1711.98
   375.9 1702.86   415.4 1693.12   435.2 1692.24   447.5 1692.68     455 1693.79
   462.5  1696.5   494.6 1707.47   504.5 1711.93   524.2 1723.55   563.8 1737.15
   613.3 1750.45   642.9 1755.06   672.6 1762.33   712.2 1774.18   751.7 1788.89
   771.5 1793.22   840.8 1822.14   850.7 1827.84   890.2 1846.47     910 1851.49
#Mann= 3 , 0 , 0
       0      .1       0   447.5    .045       0   462.5      .1       0
Bank Sta=447.5,462.5
XS Rating Curve= 0 ,0
Exp/Cntr=0.3,0.1

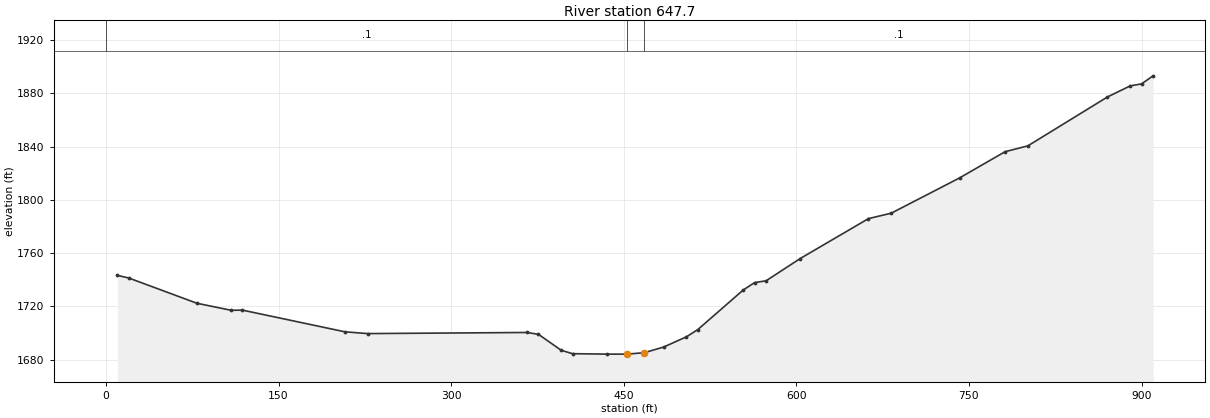
Type RM Length L Ch R = 1 ,647.7   ,227.7,233.9,240.1
XS GIS Cut Line= 3
     2052987.132      319750.068     2053280.611      320097.768
      2053574.09      320445.467
#Sta/Elev= 30
     9.9 1743.29    19.8 1741.32    79.1 1722.34   108.8 1717.07   118.7 1717.18
   207.7 1700.91   227.5 1699.57     366 1700.41   375.9 1699.01   395.7 1687.03
   405.5  1684.5   435.2 1684.16     453 1684.16     468 1685.26   484.7 1689.48
   504.5 1697.16   514.3 1702.53   553.9 1732.33   563.8 1737.88   573.7 1739.19
   603.4 1755.93   662.7 1785.88   682.5 1789.95   741.8 1816.39   781.4  1836.1
   801.2 1840.48   870.4  1877.2   890.2 1885.52   900.1 1887.03     910 1893.05
#Mann= 3 , 0 , 0
       0      .1       0     453    .045       0     468      .1       0
Bank Sta=453,468
XS Rating Curve= 0 ,0
Exp/Cntr=0.3,0.1