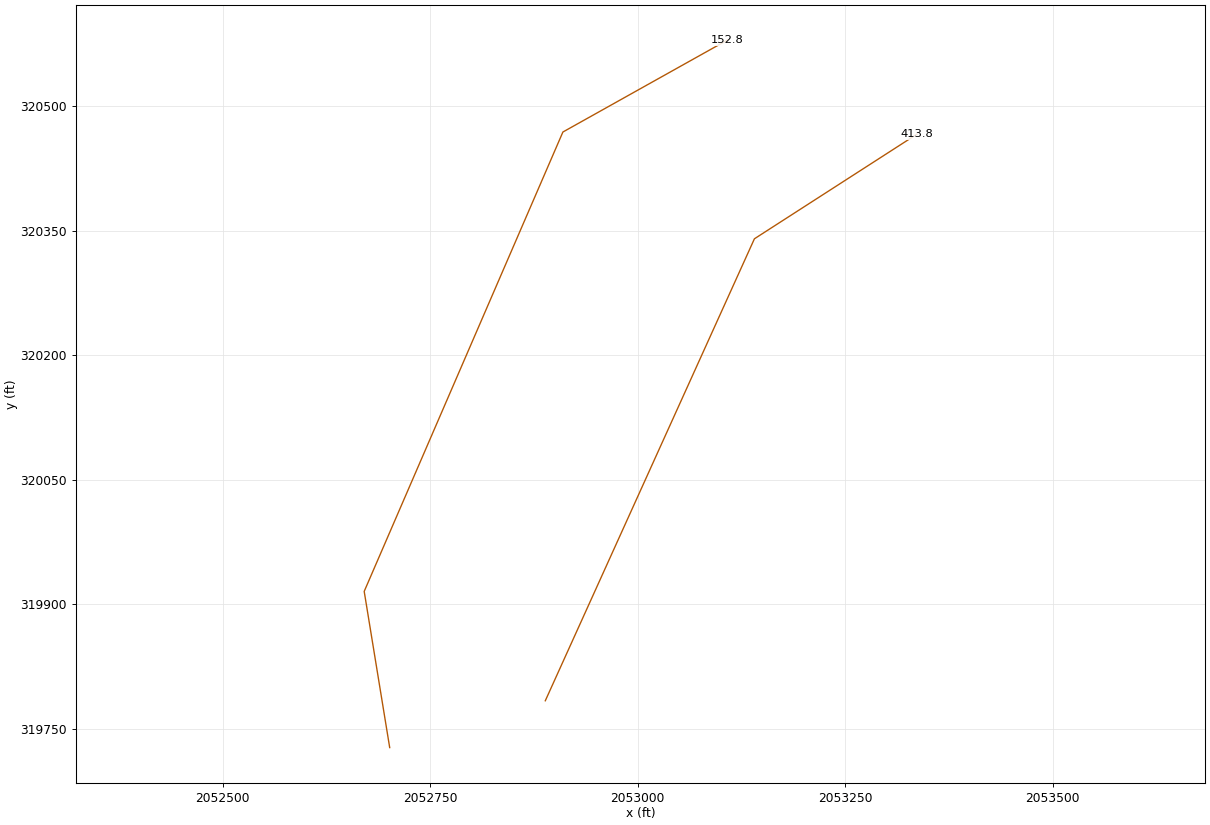
HEC-RAS study ABRMCRK.prj: ABRMCRK

--- ABRMCRK.g01 (geometry) --- (continued)

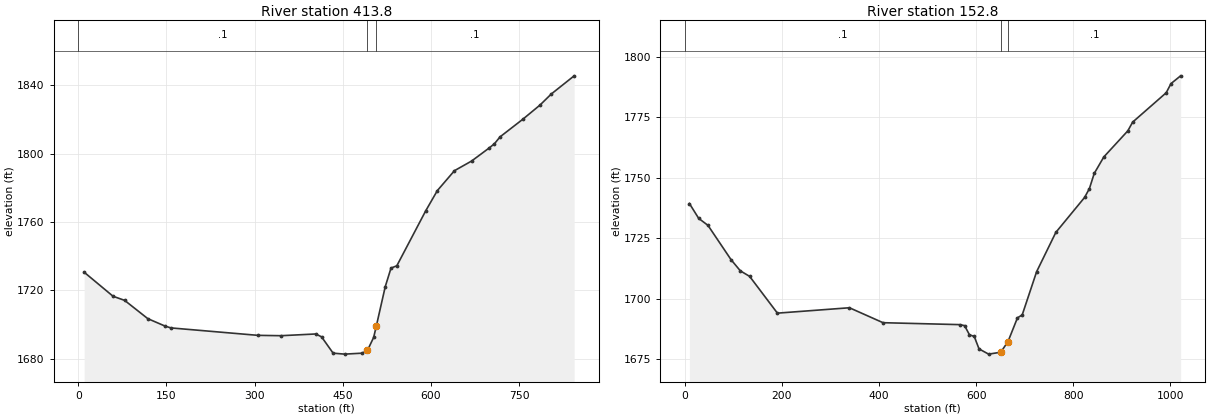
Type RM Length L Ch R = 1 ,413.8   ,260.6,261,261.4
XS GIS Cut Line= 3
     2052888.842      319783.562     2053140.796      320340.147
     2053336.548      320466.154
#Sta/Elev= 30
     9.9 1730.66    59.1  1716.6    78.8  1714.2   118.2 1703.52   147.8 1699.14
   157.7  1698.1   305.5 1693.76   344.9 1693.55     404 1694.56   413.9 1692.89
   433.6 1683.34   453.3 1682.78   482.9 1683.34     492 1684.94   502.6 1692.56
     507 1699.01   522.3 1722.19   532.1 1733.07     542 1734.41   591.2 1766.56
     611 1778.38   640.1 1790.01   669.2 1795.63   698.3 1803.05     708  1805.7
   717.7 1809.78   756.5 1820.09   785.6 1828.34     805 1834.86   843.8 1845.45
#Mann= 3 , 0 , 0
       0      .1       0     492    .045       0     507      .1       0
Bank Sta=492,507
XS Rating Curve= 0 ,0
Exp/Cntr=0.3,0.1

Type RM Length L Ch R = 1 ,152.8   ,159.4,152.8,146.2
XS GIS Cut Line= 4
      2052701.37      319727.147     2052670.647      319915.324
     2052910.047      320468.795     2053108.448      320579.706
#Sta/Elev= 30
     9.5 1739.34    28.6 1733.19    47.7  1730.3    95.3 1716.09   114.4 1711.48
   133.5  1709.2   190.7 1693.99     339 1696.22   408.2 1690.04   566.3 1689.24
   576.2 1688.82   586.1 1685.05     596 1684.35   605.9  1679.2   625.6 1677.04
   650.6 1677.82   665.6 1682.26     685 1692.05   694.8 1693.27   724.5 1711.15
     764 1727.38   823.3 1741.86   833.2 1745.53   843.1 1751.78   862.9 1758.62
   912.3  1769.4   922.2    1773   991.3 1785.15  1001.2 1788.94    1021 1792.15
#Mann= 3 , 0 , 0
       0      .1       0   650.6    .045       0   665.6      .1       0
Bank Sta=650.6,665.6
XS Rating Curve= 0 ,0
Exp/Cntr=0.3,0.1

Chan Stop Cuts=-1
Use User Specified Reach Order=0